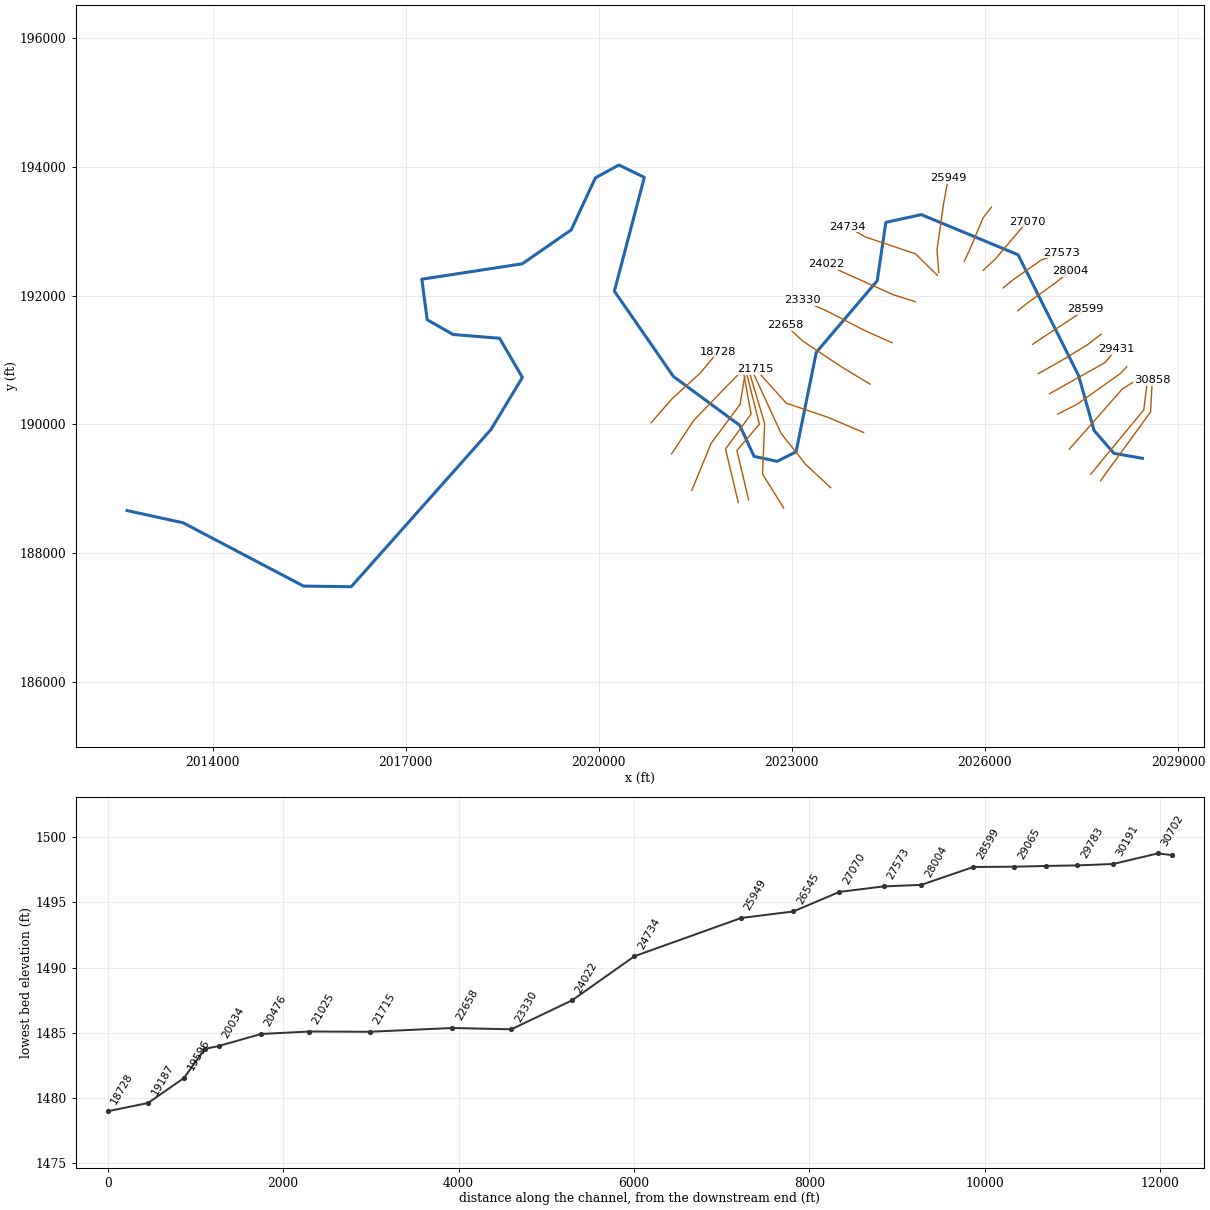
--- INDIANCK.prj (project) ---

Proj Title=INDIANCK
Current Plan=p01
Default Exp/Contr=0,0
English Units
Geom File=g01
Flow File=f01
Plan File=p01
Background Map Layer=Final_Streamlines
Background Map Layer=QC
BEGIN DESCRIPTION:
Stream Name: Indian Creek
Flood Zone: Approximate
Summers County, West Virginia
HEC-RAS Version: 5.0.7
Hydrology Method:
Regression.
Model Notes:
END DESCRIPTION:
DSS Export Rating Curves= 0
DSS Export Rating Curve Sorted= 0
DSS Export Volume Flow Curves= 0
DXF OffsetX= 0
DXF OffsetY= 0
DXF ScaleX= 0
DXF ScaleY= 0

--- INDIANCK.p01 (plan) ---

Plan Title=Floodplain
Program Version=5.07
Short Identifier=Floodplain
Geom File=g01
Flow File=f01
Subcritical Flow
K Sum by GR= 0
Std Step Tol= 0.01
Critical Tol= 0.01
Num of Std Step Trials= 20
Max Error Tol= 0.3
Flow Tol Ratio= 0.001
Split Flow NTrial= 30
Split Flow Tol= 0.02
Split Flow Ratio= 0.02
Log Output Level= 0
Friction Slope Method= 1
Unsteady Friction Slope Method= 2
Unsteady Bridges Friction Slope Method= 1
Parabolic Critical Depth
Global Vel Dist= 0 , 0 , 0
Global Log Level= 0
CheckData=True
Encroach Param=-1 ,0,0, 0
Mapping Interval=1HOUR
Computation Time Step Use Courant=        0
Computation Time Step Use Time Series=    0
Computation Time Step Count To Double=0
Computation Time Step Max Doubling=0
Computation Time Step Max Halving=0
Computation Time Step Residence Courant=0
Run HTab= 0
Run UNet= 0
Run Sediment= 0
Run PostProcess= 0
Run WQNet= 0
Run RASMapper= 0
UNET Theta= 0
UNET Theta Warmup= 0
UNET ZTol= 0
UNET ZSATol= 0
UNET MxIter= 0
UNET Max Iter WO Improvement= 0
UNET MaxInSteps= 0
UNET DtIC= 0
UNET DtMin= 0
UNET MaxCRTS= 0
UNET WFStab= 0
UNET SFStab= 0
UNET WFX= 1
UNET SFX= 1
UNET 1D Methodology=Finite Difference
UNET DSS MLevel= 1
UNET Pardiso=0
UNET DZMax Abort= 0
UNET Use Existing IB Tables= 0
UNET Froude Reduction=False
UNET Froude Limit= 0
UNET Froude Power= 0
UNET D1 Cores= 0
UNET D2 Coriolis=0
UNET D2 Cores= 0
UNET D2 Theta= 1
UNET D2 Theta Warmup= 1
UNET D2 Z Tol= 0.01
UNET D2 Volume Tol= 0.01
UNET D2 Max Iterations= 20
UNET D2 Equation= 0
UNET D2 RampUpFraction=0.1
UNET D2 TimeSlices= 1
UNET D2 BCVolumeCheck=0
UNET D1D2 MaxIter= 0
UNET D1D2 ZTol=0.01
UNET D1D2 QTol=0.1
UNET D1D2 MinQTol=1
Write IC File= 0
Write IC File at Fixed DateTime=0
Write IC File at Sim End=0
Echo Input=False
Echo Parameters=False
Echo Output=False
Write Detailed= 0
HDF Write Warmup=0
HDF Write Time Slices=0
HDF Flush=0
HDF Face Node Velocities=0
HDF Compression= 1
HDF Chunk Size= 1
HDF Spatial Parts= 1
HDF Use Max Rows=0
HDF Fixed Rows= 1
Calibration Method= 0
Calibration Iterations= 20
Calibration Max Change=0.05
Calibration Tolerance=0.2
Calibration Maximum=1.5
Calibration Minimum=0.5
Calibration Optimization Method= 1
WQ AD Non Conservative
WQ ULTIMATE=-1
WQ Max Comp Step=1HOUR
WQ Output Interval=15MIN
WQ Output Selected Increments= 0
WQ Output face flow=0
WQ Output face velocity=0
WQ Output face area=0
WQ Output face dispersion=0
WQ Output cell volume=0
WQ Output cell surface area=0
WQ Output cell continuity=0
WQ Output cumulative cell continuity=0
WQ Output face conc=0
WQ Output face dconc_dx=0
WQ Output face courant=0
WQ Output face peclet=0
WQ Output face adv mass=0
WQ Output face disp mass=0
WQ Output cell mass=0
WQ Output cell source sink temp=0
WQ Output nsm pathways=0
WQ Output nsm derived pathways=0
WQ Output MaxMinRange=-1
WQ Daily Max Min Mean=-1
WQ Daily Range=0
WQ Daily Time=0
WQ Create Restart=0
WQ Fixed Restart=0
WQ System Summary=0
WQ Write To DSS=0
WQ Use Fixed Temperature=0
Sorting and Armoring Iterations= 10
XS Update Threshold= 0.02
Bed Roughness Predictor= 0
Hydraulics Update Threshold= 0.02
Energy Slope Method= 1
Volume Change Method= 1
Sediment Retention Method= 0
XS Weighting Method= 0
Number of US Weighted Cross Sections= 1
Number of DS Weighted Cross Sections= 1
Upstream XS Weight=0
Main XS Weight=1
Downstream XS Weight=0
Number of DS XS's Weighted with US Boundary= 1
Upstream Boundary Weight= 1
Weight of XSs Associated with US Boundary= 0
Number of US XS's Weighted with DS Boundary= 1
Downstream Boundary Weight= 0.5
Weight of XSs Associated with DS Boundary= 0.5
Percentile Method= 0
Sediment Output Level= 3
Mass or Volume Output= 0
Output Increment Type= 1
Profile and TS Output Increment= 1
XS Output Flag= 0
XS Output Increment= 10
Write Gradation File= 0
Read Gradation Hotstart= 0
Write HDF5 File= 1
Write Binary Output= 1
Write DSS Sediment File= 0
SV Curve= 0
Specific Gage Flag= 0

--- INDIANCK.f01 (steady flow) ---

Flow Title=Flows
Program Version=5.07
Number of Profiles= 6
Profile Names=01pct,10pct,04pct,02pct,0_2pct,01plus
River Rch & RM=INDIANCK,Main            ,30858
   17921   10822   13493   15636   23468   26506
River Rch & RM=INDIANCK,Main            ,20476
   20007   12133   15096   17473   26146   29591
Boundary for River Rch & Prof#=INDIANCK,Main            , 1
Up Type= 0
Dn Type= 3
Dn Slope=0.00393
Boundary for River Rch & Prof#=INDIANCK,Main            , 2
Up Type= 0
Dn Type= 3
Dn Slope=0.00393
Boundary for River Rch & Prof#=INDIANCK,Main            , 3
Up Type= 0
Dn Type= 3
Dn Slope=0.00393
Boundary for River Rch & Prof#=INDIANCK,Main            , 4
Up Type= 0
Dn Type= 3
Dn Slope=0.00393
Boundary for River Rch & Prof#=INDIANCK,Main            , 5
Up Type= 0
Dn Type= 3
Dn Slope=0.00393
Boundary for River Rch & Prof#=INDIANCK,Main            , 6
Up Type= 0
Dn Type= 3
Dn Slope=0.00393
DSS Import GetInterval= 0
DSS Import GetPeak= 0
DSS Import FillOption= 0

--- INDIANCK.g01 (geometry) ---

Geom Title=Geometry
Program Version=5.07

River Reach=INDIANCK        ,Main
Reach XY= 30
2028446.86736687189471.9306230822028004.98100002189549.036999988
2027695.73599999 189904.940000022027454.85100001190759.974999997
2026515.84500003192636.1060000362025011.93900001193261.106000047
2024460.53100001193140.118999988     2024326.175192232.460000022
2023379.99400001191120.0469999972023065.75800002189573.171999993
2022771.48800001189424.7350000342022412.11299999 189502.86000004
2022190.75800002 189984.63100003     2021159.508190745.046999985
     2020242.842      192071.4362020708.22700002193840.006000027
     2020313.445194032.7050000252019947.51600001193831.981000024
     2019572.133193024.0139999942018811.70900002192496.246000029
2017250.94500001192256.6629999972017334.27900001      191626.454
     2017737.056 191397.287999992018459.27900001191338.260000037
2018813.44500003190728.885000014     2018323.862 189918.12100001
2016153.72299999187475.413000014     2015413.089187485.839000022
     2013541.932188469.5020000332012671.12400002188659.822999993

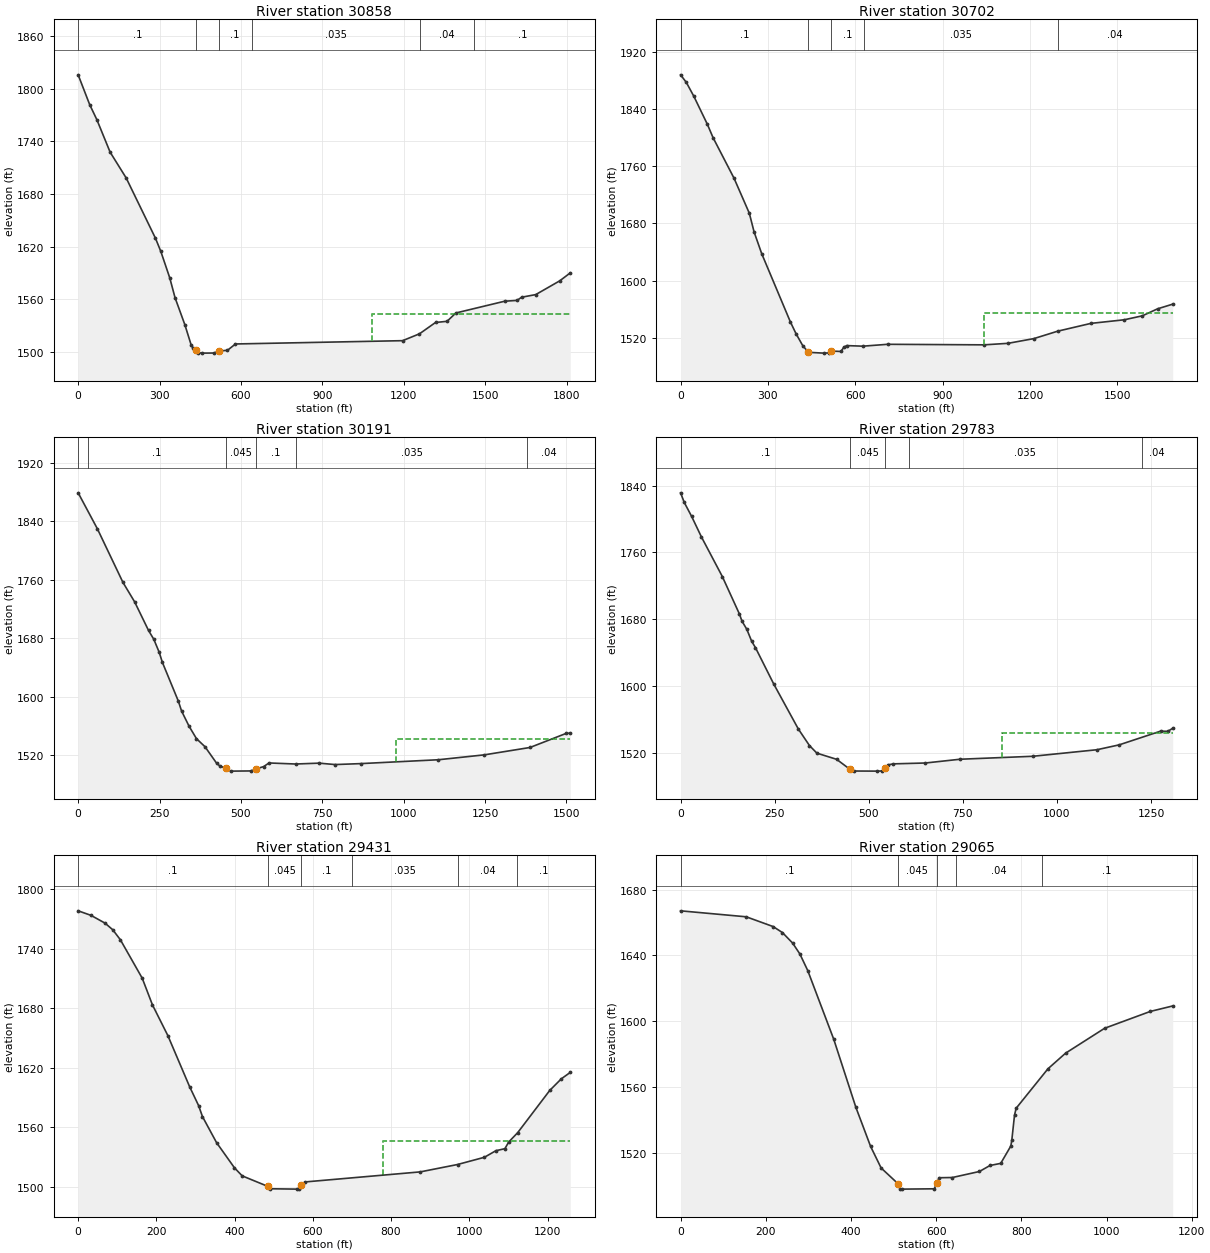
Type RM Length L Ch R = 1 ,30858   ,158.7,156,153
XS GIS Cut Line= 3
     2027797.084      189124.128     2028573.126      190191.837
     2028600.209      190684.574
#Sta/Elev= 30
       0 1815.92    42.6 1781.87    68.8 1764.88   117.9  1727.7   176.9 1698.38
     285 1629.54   304.6 1614.59   337.4 1584.56     357 1561.84     393 1531.19
     416 1508.35   422.5 1504.57   435.6 1502.55   442.2 1499.11   455.3 1498.63
   501.1 1498.74   517.5 1501.04   550.2 1501.84   579.7 1509.07  1195.5 1512.83
  1257.7 1520.66  1316.7 1533.56  1359.2  1534.9  1391.8 1544.41  1571.6 1557.82
  1617.3 1558.74  1633.7 1562.35    1686 1565.36  1774.2    1581  1813.4 1590.14
#Mann= 6 ,-1 , 0
       0      .1       0   435.6    .045       0   517.5      .1       0
     640    .035       0    1260     .04       0 1459.94      .1       0
#XS Ineff= 2 , 0
                         1083.09         1542.98
Permanent Ineff=
       F       F
Bank Sta=435.6,517.5
XS Rating Curve= 0 ,0
Exp/Cntr(USF)=0,0
Exp/Cntr=0.3,0.1

Type RM Length L Ch R = 1 ,30702   ,505,510.6,506.1
XS GIS Cut Line= 3
     2027645.348       189226.24     2028468.265       190226.24
     2028516.876      190618.602
#Sta/Elev= 30
       0 1887.73    19.7 1877.16    45.9 1857.45    91.8 1818.77   111.5 1799.96
   183.6 1743.23   236.1 1694.28   252.5 1668.14   278.7 1637.71     377  1542.5
   396.7 1525.77   419.7 1509.14   439.3 1499.89   491.6 1498.76   508.2 1499.03
     518 1501.66   550.8 1501.05   560.6 1506.96   570.5 1509.28   626.2 1508.48
   711.5  1511.1  1042.6 1510.34  1124.6 1512.46  1213.1 1519.03  1295.1 1529.42
  1409.4 1540.34  1523.8 1545.36  1585.9  1550.9  1638.2 1560.66  1690.4 1567.23
#Mann= 5 ,-1 , 0
       0      .1       0   439.3    .045       0     518      .1       0
     630    .035       0 1295.06     .04       0
#XS Ineff= 2 , 0
                         1041.83         1554.61
Permanent Ineff=
       F       F
Bank Sta=439.3,518
XS Rating Curve= 0 ,0
Exp/Cntr(USF)=0,0
Exp/Cntr=0.3,0.1

Type RM Length L Ch R = 1 ,30191   ,443,408.5,415.3
XS GIS Cut Line= 3
     2027312.015      189615.129     2028136.897       190551.31
     2028360.626      190691.518
#Sta/Elev= 30
       0 1879.23      59 1830.02   137.6 1756.52   173.6 1729.78   216.1 1690.76
   232.5 1678.47   248.9 1660.85   258.7 1647.02   307.8 1593.84   317.7  1580.3
   340.6 1559.56   363.5  1542.4   389.7 1531.36   425.7 1508.55   435.6 1504.92
   455.2 1501.76   468.3 1497.95   530.5 1498.21   546.9 1501.13   569.8 1504.14
   586.2 1509.13   668.1  1507.7   740.1 1508.88   789.3 1506.95   867.8 1508.24
  1106.9 1513.55  1247.7 1520.24  1387.9 1530.34  1498.7 1549.58  1511.8 1550.06
#Mann= 6 ,-1 , 0
       0     .12       0      30      .1       0   455.2    .045       0
   546.9      .1       0     670    .035       0 1377.74     .04       0
#XS Ineff= 2 , 0
                           976.5         1542.54
Permanent Ineff=
       F       F
Bank Sta=455.2,546.9
XS Rating Curve= 0 ,0
Exp/Cntr(USF)=0,0
Exp/Cntr=0.3,0.1

Type RM Length L Ch R = 1 ,29783   ,353.6,352.2,337.7
XS GIS Cut Line= 4
     2027131.459      190160.268     2027423.126      190306.102
     2028107.153      190792.213     2028204.376      190896.379
#Sta/Elev= 30
       0 1831.38     9.8 1819.81    29.4  1803.1    55.4 1778.52   110.9 1731.07
   156.5 1686.01     163 1677.76   176.1 1667.71   189.1 1653.27   198.9 1645.92
   247.8 1602.02     313 1548.25   342.5 1528.46   362.2 1519.39   414.6    1512
   450.7 1499.81   460.5 1497.97   522.8 1497.84   535.9 1498.06   542.4 1501.07
   552.3 1505.46   565.4 1506.55   650.6 1507.58   742.4 1512.08   935.8 1515.63
  1106.2 1523.47  1165.3  1529.3  1275.4 1545.73  1294.8 1545.54  1307.8 1549.24
#Mann= 5 ,-1 , 0
       0      .1       0   450.7    .045       0   542.4      .1       0
  606.09    .035       0 1225.26     .04       0
#XS Ineff= 2 , 0
                          854.44         1542.98
Permanent Ineff=
       F       F
Bank Sta=450.7,542.4
XS Rating Curve= 0 ,0
Exp/Cntr(USF)=0,0
Exp/Cntr=0.3,0.1

Type RM Length L Ch R = 1 ,29431   ,362.7,365.6,367.1
XS GIS Cut Line= 3
     2027002.302      190475.484     2027867.872      190961.513
     2028034.922      191167.969
#Sta/Elev= 30
       0 1778.21    32.8 1773.66    68.8 1765.79    88.5 1759.12   108.1 1748.98
   163.8 1710.33     190 1683.41   229.3 1652.53     285    1601     308 1581.95
   317.8 1570.92   353.8  1544.7   399.7 1519.24   419.4 1511.17   484.9 1500.58
   491.4 1498.16   560.2  1497.8   563.5  1497.9   570.1  1502.3   579.9 1505.03
   874.8 1515.18     970 1522.61  1038.6 1529.88  1068.1 1536.53    1091 1538.53
  1100.9 1545.33  1123.8 1554.71  1205.8 1597.28  1235.3 1608.94  1258.3 1615.44
#Mann= 6 ,-1 , 0
       0      .1       0   484.9    .045       0   570.1      .1       0
     700    .035       0     970     .04       0 1122.69      .1       0
#XS Ineff= 2 , 0
                          780.23         1545.94
Permanent Ineff=
       F       F
Bank Sta=484.9,570.1
XS Rating Curve= 0 ,0
Exp/Cntr(USF)=0,0
Exp/Cntr=0.3,0.1

Type RM Length L Ch R = 1 ,29065   ,465.7,466.4,470.3
XS GIS Cut Line= 4
2026826.91321725190786.8782762232027181.89736212190987.421267156
2027587.59352769191234.0660950842027804.27216157 191400.03270827
#Sta/Elev= 30
       0 1667.07   154.2 1663.43   217.3 1657.49   239.2 1653.82   263.2  1647.4
   280.1  1640.8   298.5 1630.74   359.6 1588.91   411.6 1547.47   446.1 1523.74
   470.8 1510.61   510.4 1501.06   515.2 1498.12   519.1 1497.74   595.9 1497.94
   601.1 1501.35   607.4 1504.67   638.1 1504.81   701.6 1508.47   726.4 1512.12
   751.6 1513.41   775.4 1524.01   777.8 1527.93     784 1542.79   787.8 1546.95
   862.4 1570.94   903.9 1580.47   995.5 1595.61  1102.7 1605.85 1155.44  1609.2
#Mann= 5 ,-1 , 0
       0      .1       0   510.4    .045       0   601.1      .1       0
  647.71     .04       0  847.71      .1       0
Bank Sta=510.4,601.1
XS Rating Curve= 0 ,0
Exp/Cntr(USF)=0,0
Exp/Cntr=0.3,0.1

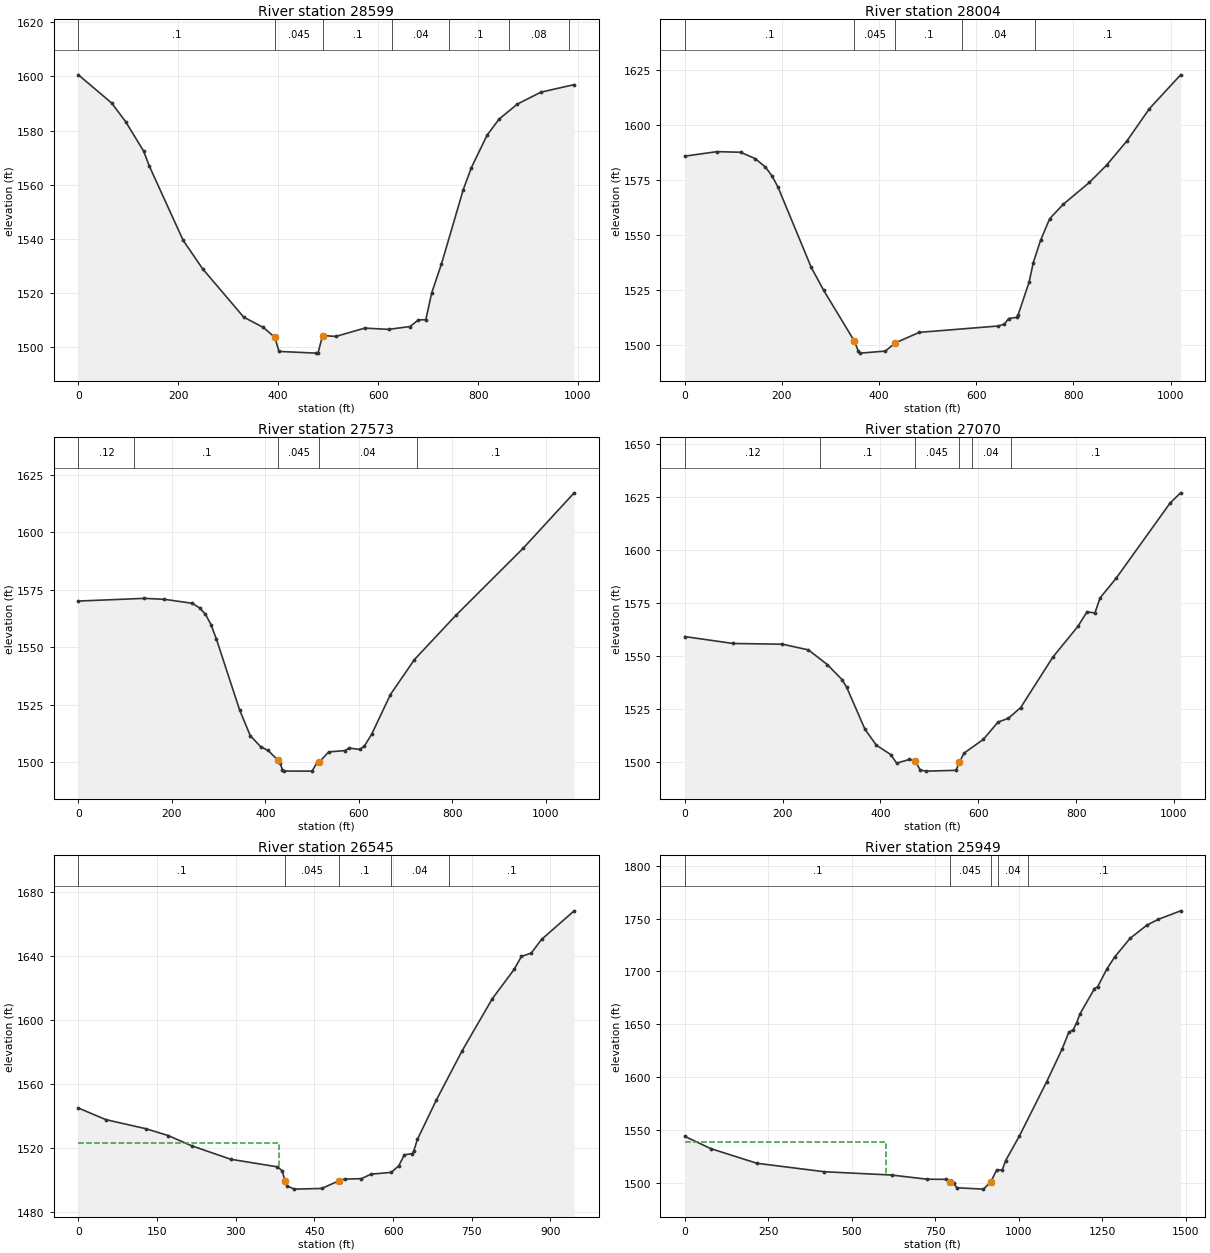
Type RM Length L Ch R = 1 ,28599   ,590.4,594.1,594.8
XS GIS Cut Line= 4
2026739.28642611191242.403166922 2026886.9474745191343.081154461
2027350.06621718191645.1151170792027564.84592393 191792.77616547
#Sta/Elev= 30
       0 1600.59    66.6 1590.19    94.8 1583.25   130.7 1572.39   142.1 1566.84
   209.7 1539.44   248.8 1528.88   331.1 1511.01   370.3 1507.21   393.3 1503.56
   401.6 1498.35     476 1497.72   479.9 1497.91   487.8 1503.52   490.5 1504.21
   515.2 1503.89   573.4 1506.97     621  1506.5     664 1507.56   680.7 1510.01
   695.4 1510.06   707.1 1519.93   726.7 1530.65   770.4 1558.17   786.5 1566.27
   818.2 1578.33   842.1 1584.22   878.5 1589.76   925.7 1594.18   992.3 1596.97
#Mann= 7 ,-1 , 0
       0      .1       0   393.3    .045       0   490.5      .1       0
  628.72     .04       0  741.62      .1       0  861.62     .08       0
  981.62      .1       0
Bank Sta=393.3,490.5
XS Rating Curve= 0 ,0
Exp/Cntr(USF)=0,0
Exp/Cntr=0.3,0.1

Type RM Length L Ch R = 1 ,28004   ,433.3,431.5,432.6
XS GIS Cut Line= 4
2026511.08298769191765.9287021262026652.03217024191880.030421337
2027108.43904709192208.9118472982027323.21875384192383.420359033
#Sta/Elev= 30
       0  1585.7    66.2 1587.75   114.7 1587.47     145 1584.58     166 1580.72
   179.3 1576.81   191.8 1571.68   260.2 1535.28   285.8 1524.85   349.2 1501.76
   357.3 1497.17   361.3 1496.35   412.7 1497.28   433.5    1501   482.6 1505.77
   645.4 1508.66   657.9 1509.48   666.5 1512.03     683 1512.55     686 1513.65
   708.8 1528.61   717.2 1537.32   732.3 1547.53   751.1 1557.35   778.7  1563.8
   832.7 1573.76   868.2 1581.62   910.4  1592.7   956.3 1607.23  1020.6 1622.59
#Mann= 5 ,-1 , 0
       0      .1       0   349.2    .045       0   433.5      .1       0
  571.34     .04       0  721.34      .1       0
Bank Sta=349.2,433.5
XS Rating Curve= 0 ,0
Exp/Cntr(USF)=0,0
Exp/Cntr=0.3,0.1

Type RM Length L Ch R = 1 ,27573   ,487.7,503,517.5
XS GIS Cut Line= 4
2026282.87954927192121.657591431  2026457.388061192262.606773986
2026880.23560867192557.9288707672027182.26957128192665.318724142
#Sta/Elev= 30
       0 1570.15   140.7 1571.32   184.2  1570.9   243.7 1569.18   259.7 1567.13
     272 1564.39   283.7 1559.93   295.4  1553.6   344.8 1522.94   367.7 1511.67
   390.4 1506.78   406.1  1505.2   427.3 1500.91   431.8 1499.55   436.7 1496.83
   439.8 1496.26   499.8 1496.23   509.9 1499.63   515.8 1500.26   535.5 1504.58
   569.9 1505.16   579.8 1506.25   601.7 1505.64   611.8 1507.08   627.6 1512.33
   667.6 1529.52   718.9 1544.71   807.5 1563.92   951.4 1593.08  1060.6 1617.19
#Mann= 5 ,-1 , 0
       0     .12       0     120      .1       0   427.3    .045       0
   515.8     .04       0  724.32      .1       0
Bank Sta=427.3,515.8
XS Rating Curve= 0 ,0
Exp/Cntr(USF)=0,0
Exp/Cntr=0.3,0.1

Type RM Length L Ch R = 1 ,27070   ,500.1,525.1,536.5
XS GIS Cut Line= 4
2025974.13372081192396.8440907052026162.06596422192571.352602439
2026464.09992684192927.0814917442026652.03217024 193148.57306433
#Sta/Elev= 30
       0 1559.28    98.7 1556.02   199.6 1555.68   252.7    1553   291.2  1546.1
   321.8 1538.89   331.1 1535.27   368.3 1515.55   391.6 1508.05   420.9 1503.64
   433.1 1499.57   459.1 1501.32   470.7 1500.75   481.2 1496.35     494 1495.81
   554.3 1496.19   561.5 1500.02   570.8 1504.29   610.3 1510.79   640.4 1518.96
   661.2 1520.69   686.6 1525.79   752.3 1549.56   803.6 1564.07   822.2 1570.96
   838.4 1570.41   848.8 1577.47   881.4 1586.67   992.1 1622.27  1013.6 1627.08
#Mann= 6 ,-1 , 0
       0     .12       0  276.46      .1       0   470.7    .045       0
   561.5      .1       0  586.46     .04       0  666.46      .1       0
Bank Sta=470.7,561.5
XS Rating Curve= 0 ,0
Exp/Cntr(USF)=0,0
Exp/Cntr=0.3,0.1

Type RM Length L Ch R = 1 ,26545   ,577.2,595.7,617
XS GIS Cut Line= 4
2025678.81162403192537.7932732592025759.35401406192705.589919158
2025974.13372081 193215.69172269 2026101.6591717193376.776502753
#Sta/Elev= 30
       0 1544.95    52.5 1537.69     129    1532   171.1 1527.78   216.5 1521.31
   290.4 1512.96   379.4 1508.22   388.8 1505.74   393.6 1499.68   397.2 1496.44
   411.3 1494.31   463.9 1494.73   496.9 1499.52   507.6 1500.57   539.6 1500.84
   557.4  1503.6   596.6  1504.8   610.8 1508.91   621.5 1515.76   636.8  1516.5
   639.3 1518.09   646.4 1525.41   682.3 1549.85   731.8 1580.82     789 1613.13
   830.6 1631.43   844.6 1639.57   863.3 1641.64     883  1650.2   945.1 1668.03
#Mann= 5 ,-1 , 0
       0      .1       0   393.6    .045       0   496.9      .1       0
  596.13     .04       0  706.13      .1       0
#XS Ineff= 2 , 0
          383.23 1523.04
Permanent Ineff=
       F       F
Bank Sta=393.6,496.9
XS Rating Curve= 0 ,0
Exp/Cntr(USF)=0,0
Exp/Cntr=0.3,0.1

Type RM Length L Ch R = 1 ,25949   ,1088.9,1215.7,1333.4
XS GIS Cut Line= 4
2025282.81153971192356.5728956892025255.96407637192712.301784994
2025356.64206391193423.759563604 2025430.4725881193826.471513761
#Sta/Elev= 30
       0 1543.76    77.9 1532.15   216.1 1518.28   417.2  1510.3   619.3 1507.15
   726.2 1503.19   781.7 1503.07  793.881500.474   804.9 1499.18   814.8 1495.09
   894.4 1493.81  915.741500.474   934.1 1511.98   950.7 1511.99   960.6 1520.77
  1002.2 1544.31  1083.3  1595.3    1130 1626.55    1150 1642.45  1163.3 1644.79
  1173.2 1651.24  1183.3 1659.76  1226.7 1683.61  1236.7 1685.62  1263.4 1702.03
  1286.7 1713.36  1333.4  1731.3  1383.5 1743.68  1416.8 1749.12  1484.7 1757.31
#Mann= 5 ,-1 , 0
       0      .1       0  793.88    .045       0  915.74      .1       0
  936.74     .04       0 1026.74      .1       0
#XS Ineff= 2 , 0
           601.2 1538.35
Permanent Ineff=
       F       F
Bank Sta=793.88,915.74
XS Rating Curve= 0 ,0
Exp/Cntr(USF)=0,0
Exp/Cntr=0.3,0.1

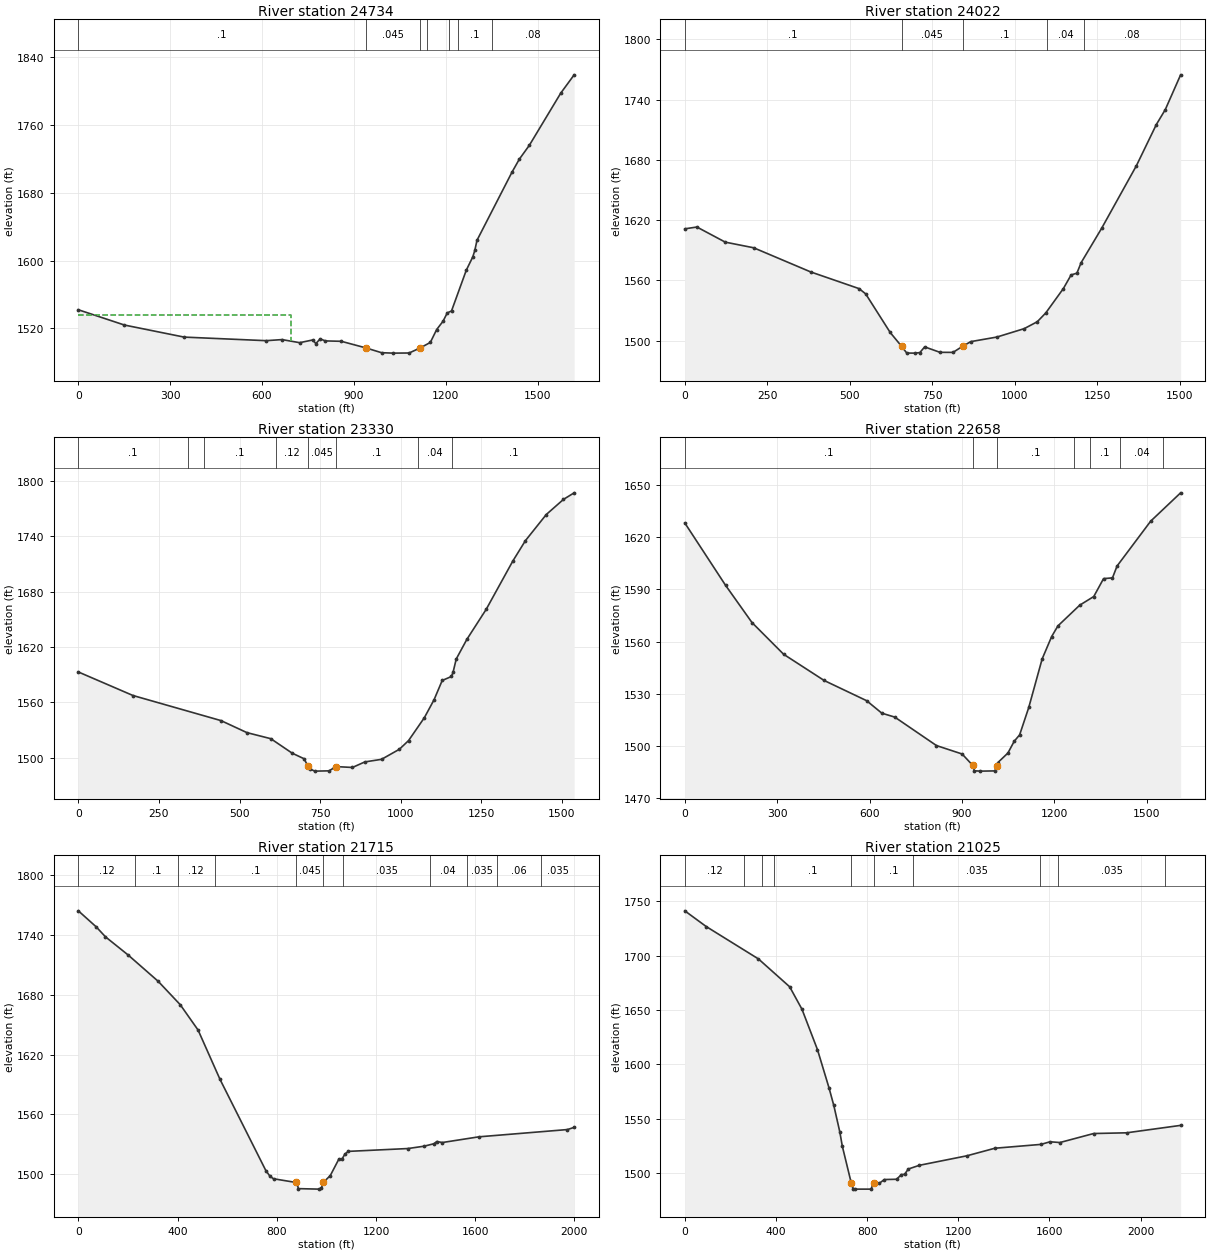
Type RM Length L Ch R = 1 ,24734   ,704,711.1,680
XS GIS Cut Line= 4
 2025262.6759422192316.3017006732024920.37078457192651.894992471
 2024141.7943476192913.6577600722023866.60784833193074.742540135
#Sta/Elev= 30
       0    1542   150.7 1523.98   345.6 1509.77   613.3 1505.56   665.2 1506.83
     723 1503.21   765.6 1506.39   775.9 1502.12   789.8 1507.66   807.1 1505.28
     859 1504.82  939.771496.981   990.6 1491.37  1028.6 1490.88  1080.5 1491.04
 1116.561496.982  1149.8 1503.49  1170.5 1518.68  1191.3 1528.46  1205.1 1538.31
    1219 1540.61  1267.4 1588.78  1288.5 1604.33  1295.1 1611.97  1302.2 1623.89
  1416.2 1703.98  1440.4 1719.47  1473.3 1735.92  1575.9 1797.43  1619.6 1818.95
#Mann= 7 ,-1 , 0
       0      .1       0  939.77    .045       0 1116.56      .1       0
 1139.37     .08       0 1209.37     .04       0 1239.37      .1       0
 1350.77     .08       0
#XS Ineff= 2 , 0
           693.7 1535.96
Permanent Ineff=
       F       F
Bank Sta=939.77,1116.56
XS Rating Curve= 0 ,0
Exp/Cntr(USF)=0,0
Exp/Cntr=0.3,0.1

Type RM Length L Ch R = 1 ,24022   ,692.8,692,680
XS GIS Cut Line= 4
2024920.37078457191906.8778846812024578.06562694192014.267738056
2023786.06545829192369.9966273612023537.72642237192490.810212408
#Sta/Elev= 30
       0 1611.28    36.7 1613.08   122.7 1598.02   208.7 1592.42   381.6 1568.37
   528.4 1551.72   548.3 1546.52   622.7 1508.05   657.5 1494.16   672.9 1487.58
   698.1  1487.5   712.5 1488.03   727.2 1493.71   773.6  1488.3   813.2 1488.24
   841.9 1494.27   867.1 1498.97   946.2 1503.52    1029 1511.89  1068.5 1518.75
  1094.3 1527.53  1147.7 1551.84  1171.2 1565.41  1188.6  1567.1  1201.6 1577.65
  1263.3 1611.61  1369.1 1674.17  1429.5 1715.15  1456.6    1730  1503.1 1764.64
#Mann= 5 ,-1 , 0
       0      .1       0   657.5    .045       0   841.9      .1       0
 1098.76     .04       0 1208.76     .08       0
Bank Sta=657.5,841.9
XS Rating Curve= 0 ,0
Exp/Cntr(USF)=0,0
Exp/Cntr=0.3,0.1

Type RM Length L Ch R = 1 ,23330   ,675.7,672.4,659
XS GIS Cut Line= 4
2024557.93002943191269.2506302662024135.08248176191457.182873672
2023524.30269069191772.6405679622023168.57380139191927.013482189
#Sta/Elev= 30
       0 1592.85   169.5 1567.31   442.4  1540.1     523 1527.04     597 1520.47
   663.3 1504.76   700.3 1498.68   711.3 1491.21   718.7 1487.52   733.5 1485.28
   777.8 1485.59   799.1 1490.21   850.2 1489.25   888.6 1495.27   940.4 1498.07
   995.7 1508.98  1024.2 1518.39  1073.2 1543.21  1103.5  1562.8  1128.6  1583.6
  1157.2 1587.93  1162.2 1592.38  1172.2 1606.96    1205 1628.16  1265.2 1660.87
  1347.4 1713.03  1386.6 1735.23  1451.5 1763.66  1504.8 1780.06  1537.9 1787.17
#Mann= 8 ,-1 , 0
       0      .1       0     340     .12       0     390      .1       0
  612.73     .12       0   711.3    .045       0   799.1      .1       0
 1052.73     .04       0 1160.16      .1       0
Bank Sta=711.3,799.1
XS Rating Curve= 0 ,0
Exp/Cntr(USF)=0,0
Exp/Cntr=0.3,0.1

Type RM Length L Ch R = 1 ,22658   ,933.7,943.5,955.7
XS GIS Cut Line= 4
 2024215.6248718190624.9115100152023772.64172662190893.386143453
2023168.57380139 191296.098093612022900.09916795 191544.43712954
#Sta/Elev= 30
       0 1628.32   132.2 1592.44   218.2 1570.94   320.9 1552.68   452.5 1537.58
   590.2 1525.96   639.6 1518.76   681.6  1516.5   817.1  1500.1   900.4 1495.24
   934.3 1488.77   940.3 1485.57   959.5 1485.38  1006.6 1485.51  1012.8 1488.24
    1016 1490.24  1049.1 1495.82  1069.4 1502.58    1087 1506.26  1116.8 1522.12
  1160.1 1549.98  1191.1 1562.92  1211.4 1569.04  1282.2 1580.97  1327.7 1585.94
  1359.5 1596.25  1388.5 1596.69  1403.3  1603.5  1512.5 1629.35  1609.7 1645.67
#Mann= 7 ,-1 , 0
       0      .1       0   934.3    .045       0  1012.8      .1       0
 1263.99     .04       0 1313.99      .1       0 1413.99     .04       0
 1553.99      .1       0
Bank Sta=934.3,1012.8
XS Rating Curve= 0 ,0
Exp/Cntr(USF)=0,0
Exp/Cntr=0.3,0.1

Type RM Length L Ch R = 1 ,21715   ,722.5,689.1,652
XS GIS Cut Line= 4
2024114.94688426 189873.182536392023564.57388571190108.097840648
2022913.52289962190329.5894132342022436.98042527190859.826814273
#Sta/Elev= 30
       0 1763.98      72 1747.94   109.5  1737.9   200.4  1719.8   321.7 1693.41
   410.9  1669.9   482.8 1644.51   571.4 1594.97   755.9 1503.72   772.8 1497.95
     787 1495.47   877.2 1491.78   880.6 1491.21   887.5 1485.58   970.7 1485.09
   979.7 1485.89   987.4 1491.74  1015.8 1498.68  1050.4  1515.2  1064.3 1515.73
  1074.7 1520.19  1088.5 1522.92  1329.1 1525.77  1394.1 1528.12  1433.6 1530.58
  1445.2  1532.8  1467.7  1531.8  1614.7  1537.5    1972 1544.79    1999 1546.99
#Mann= 11 ,-1 , 0
       0     .12       0     230      .1       0     400     .12       0
     550      .1       0   877.2    .045       0   987.4      .1       0
 1068.41    .035       0 1416.11     .04       0 1566.11    .035       0
 1686.11     .06       0 1866.11    .035       0
Bank Sta=877.2,987.4
XS Rating Curve= 0 ,0
Exp/Cntr(USF)=0,0
Exp/Cntr=0.3,0.1

Type RM Length L Ch R = 1 ,21025   ,595.2,549.5,500.6
XS GIS Cut Line= 4
2023604.84508072189014.0637093892023215.55686224 189376.50446453
2022832.98050959189859.7588047182022403.42109609190792.708155914
#Sta/Elev= 30
       0 1741.24    93.8  1726.8   323.1 1696.97   460.1 1671.33   514.2 1650.61
   582.1 1613.47   632.6 1578.39   653.7 1562.14   680.2 1537.65   690.9 1524.75
   730.5 1490.59   738.3 1485.68   746.9 1485.11     817 1485.11   828.2 1490.62
   854.1 1490.61   875.7 1493.94   929.1 1494.19   950.3 1498.49   964.1 1498.65
   980.4  1503.6    1029 1507.03  1237.5 1515.78  1360.3 1522.74  1562.6 1526.28
  1602.3 1528.69  1645.7    1528  1793.7 1536.28  1938.2 1536.94  2175.3 1543.78
#Mann= 10 ,-1 , 0
       0     .12       0     260      .1       0     340     .12       0
     390      .1       0   730.5    .045       0   828.2      .1       0
 1001.89    .035       0 1558.25     .06       0 1638.25    .035       0
 2108.25     .04       0
Bank Sta=730.5,828.2
XS Rating Curve= 0 ,0
Exp/Cntr(USF)=0,0
Exp/Cntr=0.3,0.1

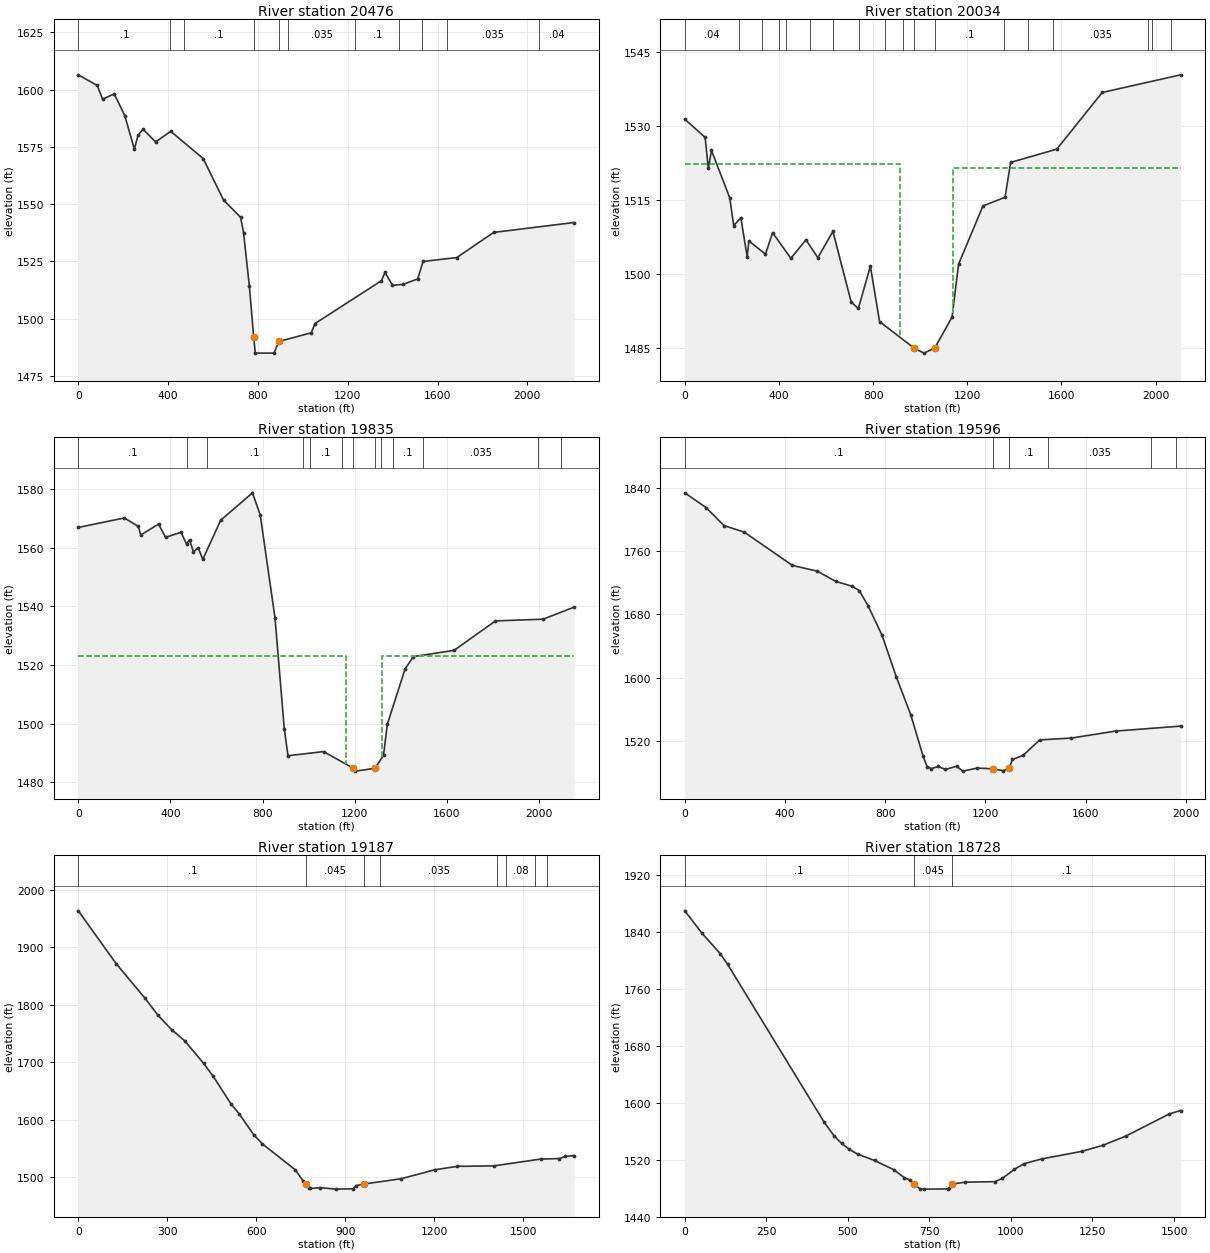
Type RM Length L Ch R = 1 ,20476   ,533.3,484.7,436.1
XS GIS Cut Line= 4
2022873.25170461188698.6060150992022544.37027865189228.843416139
2022577.92960783190014.131718944 2022349.7261694190779.284424242
#Sta/Elev= 30
       0 1606.47    84.2 1601.81     108 1595.86   160.1 1598.15     207 1588.61
   249.5 1574.06   265.9 1580.07   288.1 1582.75   343.9 1577.17   411.6 1581.78
     556 1569.92     647 1551.74   722.5 1544.26   735.9  1537.6   761.9 1514.07
   781.11491.783   788.2 1484.94   871.3 1484.92   893.3    1490  1037.7 1493.82
  1053.9 1497.82  1349.7 1516.53  1366.1 1520.18    1399 1514.58  1445.2 1514.91
  1511.5 1517.33  1535.4 1524.95  1685.2 1526.65  1850.4 1537.65  2208.4 1541.97
#Mann= 11 ,-1 , 0
       0      .1       0     410     .12       0     470      .1       0
   781.1    .045       0   893.3      .1       0  933.95    .035       0
 1233.95      .1       0 1429.96     .06       0 1529.96     .04       0
 1639.96    .035       0 2049.96     .04       0
Bank Sta=781.1,893.3
XS Rating Curve= 0 ,0
Exp/Cntr(USF)=0,0
Exp/Cntr=0.5,0.3

Type RM Length L Ch R = 1 ,20034   ,137.6,155.8,148.8
XS GIS Cut Line= 4
2022328.93119683188826.5067849312022146.73177908189593.713059518
2022496.03368726190002.3822089882022305.80573293190759.432738659
#Sta/Elev= 30
       01531.444  86.4651527.755  99.9541521.483 113.4421525.103     1911515.489
  207.861509.875 238.209 1511.45 265.1861503.475  271.931506.749 342.7441504.082
 373.0921508.426  450.651503.229  514.72 1506.98 565.301 1503.35 629.3711508.695
 706.9281494.364 737.2771493.054 788.5441501.618 827.5561490.397 973.9921485.023
1016.4121483.994 1062.021485.0251135.5761491.3021163.1551502.0291266.7391513.843
1360.7721515.6081384.452 1522.681580.6551525.3751773.4761536.8612106.7371540.444
#Mann= 18 ,-1 , 0
       0     .04       0     230     .06       0     330      .1       0
     400     .06       0     430     .04       0     530      .1       0
     630     .04       0     740      .1       0  848.54     .04       0
  928.54      .1       0 973.992    .045       0 1062.02      .1       0
 1356.15     .08       0 1456.15     .04       0 1566.15    .035       0
 1966.15     .04       0 1986.15     .06       0 2066.15     .08       0
#XS Ineff= 2 , 0
          913.17 1522.36 1137.72         1521.57
Permanent Ineff=
       F       F
Bank Sta=973.992,1062.02
XS Rating Curve= 0 ,0
Exp/Cntr(USF)=0,0
Exp/Cntr=0.5,0.3

Type RM Length L Ch R = 1 ,19835   ,243.8,239.1,233.9
XS GIS Cut Line= 4
2022167.04932373188784.7990004542021970.16856064 189617.73917272
2022366.49752638 190159.388759242022256.40614702190775.900483735
#Sta/Elev= 30
       01566.875 200.0971570.109 260.7791567.195 270.8931564.294 348.4311567.997
 378.7721563.487 446.1971565.238 469.7961561.193 483.2811562.634 500.1371558.467
 520.3641559.985 540.592 1555.99  618.131569.328 756.3511578.672 790.0631571.084
 854.1171536.065 894.4051498.199 910.6661489.0281065.148 1490.45 1194.22 1484.76
1203.3741483.781 1288.741484.7491325.4451489.1831341.5891499.681 1418.831518.587
1455.4181522.8471631.6311524.9471811.5991535.0022018.228 1535.59 2153.321539.695
#Mann= 13 ,-1 , 0
       0      .1       0     470     .04       0     560      .1       0
  975.89     .04       0 1005.89      .1       0 1145.89     .04       0
 1194.22    .045       0 1288.74      .1       0 1315.89     .04       0
 1365.89      .1       0 1495.89    .035       0 1997.06     .06       0
 2097.06     .08       0
#XS Ineff= 2 , 0
         1163.01 1523.15 1320.96         1523.15
Permanent Ineff=
       F       F
Bank Sta=1194.22,1288.74
XS Rating Curve= 0 ,0
Exp/Cntr(USF)=0,0
Exp/Cntr=0.5,0.3

Type RM Length L Ch R = 1 ,19596   ,453.4,409.2,388.6
XS GIS Cut Line= 4
2021447.09297381188975.9523927992021746.54152571189706.959151843
2022195.71435356190310.2599108132022266.17283636190741.818117959
#Sta/Elev= 30
       0 1833.96    85.7 1815.13   156.3 1792.53   237.9 1784.13   429.3 1742.09
   528.6 1734.76     603 1721.75   666.9  1715.8   696.9 1710.09   732.1 1690.63
   787.4 1653.69   843.8 1601.36   902.5 1552.52   950.6 1501.28     967 1487.37
   984.5 1484.74    1012 1487.41  1040.6 1483.68    1085 1487.74  1110.1 1481.54
  1167.4 1485.38  1228.4 1484.55  1271.8 1482.11  1293.8 1484.87  1308.1 1496.28
  1351.5 1501.72  1416.9 1521.09  1543.4 1523.42  1719.6 1532.24  1979.4 1538.55
#Mann= 6 ,-1 , 0
       0      .1       0  1228.4    .045       0  1293.8      .1       0
 1449.96    .035       0 1862.11     .06       0 1962.11     .08       0
Bank Sta=1228.4,1293.8
XS Rating Curve= 0 ,0
Exp/Cntr(USF)=0,0
Exp/Cntr=0.3,0.1

Type RM Length L Ch R = 1 ,19187   ,469.8,459.2,454.3
XS GIS Cut Line= 4
2021130.02980122189539.6202551942021477.91856004190063.655221015
2021944.70600859190548.0572902612022204.52166391190812.276600759
#Sta/Elev= 30
       0 1963.68   128.2  1871.4   225.6 1811.21   268.9  1781.9   314.5  1757.2
   359.3 1737.34   422.5 1698.41   454.5 1676.09   515.7 1627.25   541.8 1611.09
   591.8  1574.2   619.9 1558.71   731.8  1513.2   759.1 1493.06  768.731488.422
   777.8 1481.83     783 1480.77   816.1 1482.18   868.2 1479.63   926.3 1480.23
   936.8 1485.67   961.91488.425  1088.7 1497.69  1202.4 1513.32  1278.5 1519.26
  1401.4 1520.07  1559.7 1531.93  1622.4 1532.79  1641.8 1536.42  1672.3 1538.03
#Mann= 8 ,-1 , 0
       0      .1       0  768.73    .045       0   961.9      .1       0
    1019    .035       0 1411.71     .06       0 1441.71     .08       0
 1541.71     .06       0 1581.71     .08       0
Bank Sta=768.73,961.9
XS Rating Curve= 0 ,0
Exp/Cntr(USF)=0,0
Exp/Cntr=0.3,0.1

Type RM Length L Ch R = 1 ,18728   ,459.4,458.3,456
XS GIS Cut Line= 4
2020812.96662862 190024.022324442021138.83711157190398.333014312
2021579.20262906190799.0656352342021852.22924991191129.339773356
#Sta/Elev= 30
       0 1870.12    53.2  1838.4   109.1 1809.69   131.2 1794.98   427.6 1572.86
   457.9  1553.8   481.1 1543.13   504.9 1534.76   529.9 1528.29   581.8 1519.24
   641.4 1506.13   673.4 1494.98   691.2 1491.73   701.8 1486.11   722.2 1479.19
   734.3    1479   806.3 1479.28     811 1480.51   819.8 1486.06   859.7 1488.81
   950.3 1489.48   973.5 1494.01  1010.8 1506.92    1040  1514.7  1094.3 1521.49
  1216.9 1532.05  1280.7  1540.4    1353 1553.72    1485 1584.62  1520.2 1589.49
#Mann= 3 ,-1 , 0
       0      .1       0   701.8    .045       0   819.8      .1       0
Bank Sta=701.8,819.8
XS Rating Curve= 0 ,0
Exp/Cntr(USF)=0,0
Exp/Cntr=0.3,0.1