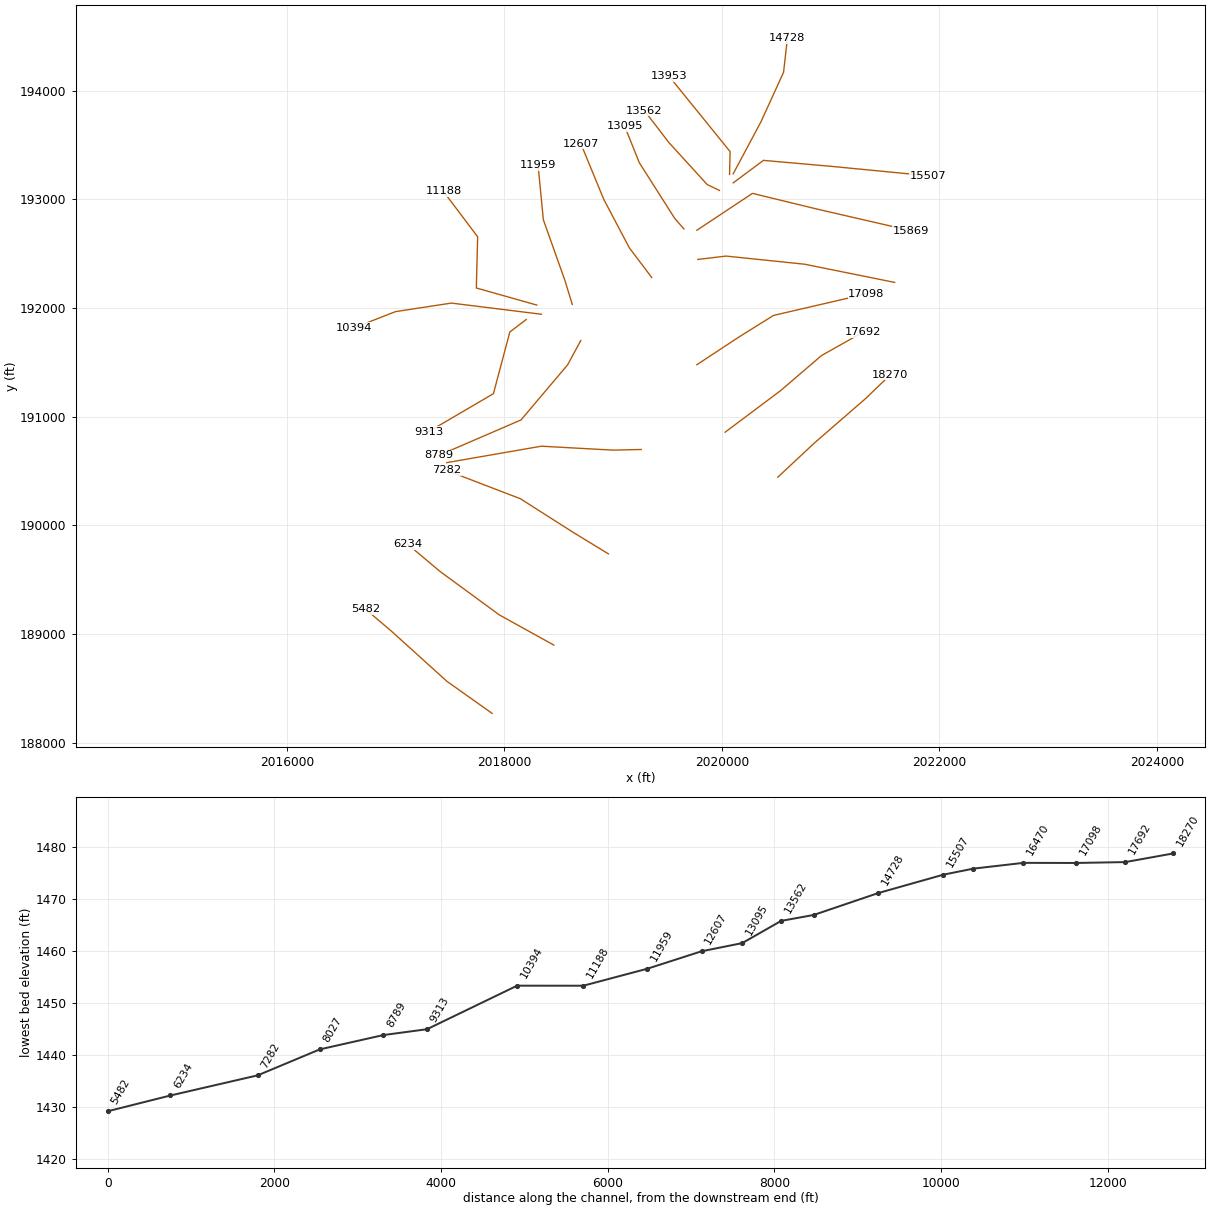
HEC-RAS study INDIANCK.prj: INDIANCK

--- INDIANCK.g01 (geometry) --- (continued)

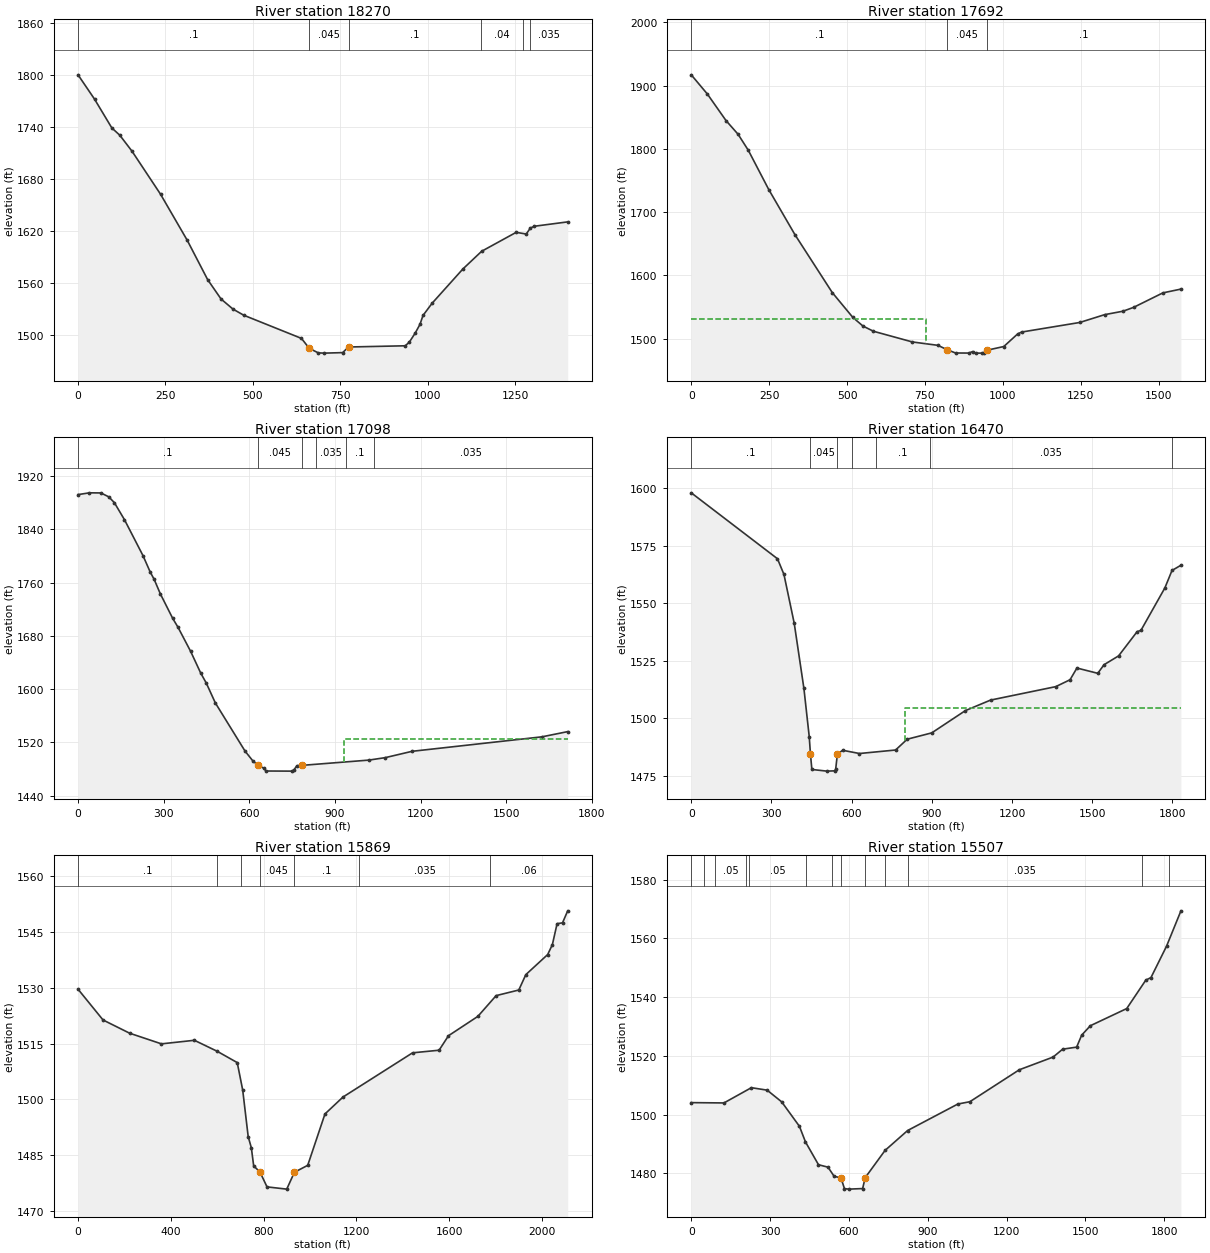
Type RM Length L Ch R = 1 ,18270   ,576,577.9,578.1
XS GIS Cut Line= 4
2020513.51807672190442.3695660622020852.59952519190759.432738659
2021319.38697374191164.5690147562021548.37704284191384.751773504
#Sta/Elev= 30
       0 1800.04    47.3 1771.93    96.7 1738.69   119.2 1730.42   154.3 1711.91
     236 1662.16   312.3    1609   370.6 1563.62   408.9 1541.26     443 1529.61
   473.7 1522.56   638.8 1495.79   661.1 1484.34   686.9 1479.07   703.9 1478.78
   756.5 1479.36   773.4 1485.85   935.6 1487.25   947.2 1491.49   963.5 1501.58
   977.6 1511.93   986.3 1522.25  1012.2 1536.29  1100.1 1575.82    1154 1596.36
  1252.7 1618.21  1281.6 1616.27  1293.2 1623.18  1304.8 1625.25    1400 1630.29
#Mann= 6 ,-1 , 0
       0      .1       0   661.1    .045       0   773.4      .1       0
 1152.31     .04       0 1272.31     .06       0 1292.31    .035       0
Bank Sta=661.1,773.4
XS Rating Curve= 0 ,0
Exp/Cntr(USF)=0,0
Exp/Cntr=0.3,0.1

Type RM Length L Ch R = 1 ,17692   ,607.8,593.3,577.8
XS GIS Cut Line= 4
2020029.11600748190856.3131525082020539.94000777 191239.43115273
2020914.25069764191560.8979805022021297.36869787191776.677084076
#Sta/Elev= 30
       0 1916.97    51.9 1886.49   111.5 1844.72   150.3    1823   183.1 1797.71
   248.7 1735.67   332.9 1664.23   452.6  1572.8   518.2 1533.78     551 1519.92
   584.8 1511.66   709.8 1494.75   791.3 1489.45   822.2 1482.34   848.2 1477.32
   891.4 1477.22     903  1479.6   912.3 1477.12   933.2 1477.11     939  1477.4
   947.6 1481.54    1003 1487.54  1047.2 1507.29  1060.1 1510.41  1246.6 1525.53
  1327.1 1537.96  1385.7 1543.37  1419.6 1549.43  1513.7 1572.34  1571.6 1578.32
#Mann= 3 ,-1 , 0
       0      .1       0   822.2    .045       0   947.6      .1       0
#XS Ineff= 2 , 0
          751.86 1530.26
Permanent Ineff=
       F       F
Bank Sta=822.2,947.6
XS Rating Curve= 0 ,0
Exp/Cntr(USF)=0,0
Exp/Cntr=0.3,0.1

Type RM Length L Ch R = 1 ,17098   ,681.1,628.5,571.9
XS GIS Cut Line= 4
2019769.30035215191477.2285321782020156.82200755191732.640532326
2020473.88518015191930.8050151992021328.19428409192128.969498073
#Sta/Elev= 30
       0 1892.07    39.9 1894.74      80 1894.58   107.5 1888.74   127.2 1880.03
   162.6 1854.46   227.5 1800.48   252.9 1775.75   266.5 1764.99   288.3 1743.09
   331.7 1706.16     350 1693.05   394.4 1656.75   429.7 1624.17   449.4 1608.95
     481 1579.29     585 1506.98   612.7 1492.08  631.191485.626   650.1 1481.46
   658.5 1477.11   747.7 1476.94   754.8 1478.09   766.7 1485.04  785.511485.626
  1018.6  1493.5  1075.8 1497.16  1170.1  1506.7  1624.8 1528.43    1715 1536.25
#Mann= 6 ,-1 , 0
       0      .1       0  631.19    .045       0  785.51      .1       0
  834.12    .035       0  938.02      .1       0 1038.02    .035       0
#XS Ineff= 2 , 0
                          930.95            1525
Permanent Ineff=
       F       F
Bank Sta=631.19,785.51
XS Rating Curve= 0 ,0
Exp/Cntr(USF)=0,0
Exp/Cntr=0.3,0.1

Type RM Length L Ch R = 1 ,16470   ,602.4,600.6,594.1
XS GIS Cut Line= 4
 2019778.1076625 192446.032670672020037.92331783192476.858256895
2020760.12276652 192401.996118922021588.00993941192234.657222272
#Sta/Elev= 30
       0 1597.96   322.6  1569.3   346.8  1562.5   385.3 1541.24   421.5 1512.93
   441.4 1492.01  446.021484.384   451.3 1477.68   507.3 1476.96     537 1477.08
   540.3 1477.72  546.871484.386   566.7 1486.02   629.4 1484.62   764.6 1486.14
   808.1 1490.84   899.9 1493.59  1025.7 1503.27  1120.1 1507.85  1363.8 1513.69
  1417.4 1516.69  1443.1 1521.78  1521.1 1519.49  1544.6 1523.23    1599 1527.06
  1668.6 1537.63  1682.5 1538.13  1772.2 1556.61  1798.9 1564.21  1832.3 1566.47
#Mann= 7 ,-1 , 0
       0      .1       0  446.02    .045       0  546.87      .1       0
  601.64    .035       0  691.64      .1       0  891.64    .035       0
 1797.71     .04       0
#XS Ineff= 2 , 0
                          799.43         1504.21
Permanent Ineff=
       F       F
Bank Sta=446.02,546.87
XS Rating Curve= 0 ,0
Exp/Cntr(USF)=0,0
Exp/Cntr=0.3,0.1

Type RM Length L Ch R = 1 ,15869   ,359.8,362.3,370.4
XS GIS Cut Line= 4
2019769.30035215192714.6556363432020280.12435245193053.737084815
2020896.63607694192904.0128088662021737.73421536192710.251981168
#Sta/Elev= 30
       0 1529.61   107.8 1521.33   222.6 1517.77   359.5 1514.91   501.6 1515.87
     600 1512.91   686.3 1509.87   709.9 1502.46   733.5 1489.96   747.1 1486.96
   757.2 1482.08   784.2 1480.47   814.6 1476.45   899.7 1475.85   932.7 1480.38
   990.1 1482.25  1064.4 1496.06  1142.1 1500.61    1442  1512.5  1556.3  1513.2
  1596.9  1517.1  1723.5  1522.3  1802.2 1527.88  1899.9 1529.39  1930.2 1533.52
  2024.5 1538.93  2044.7  1541.6  2064.9 1547.22  2088.4 1547.45  2110.7 1550.68
#Mann= 7 ,-1 , 0
       0      .1       0     600    .035       0  703.12      .1       0
   784.2    .045       0   932.7      .1       0 1213.12    .035       0
 1777.55     .06       0
Bank Sta=784.2,932.7
XS Rating Curve= 0 ,0
Exp/Cntr(USF)=0,0
Exp/Cntr=0.3,0.1

Type RM Length L Ch R = 1 ,15507   ,727.4,778.8,846.1
XS GIS Cut Line= 4
2020103.48885043193150.6174986642020381.40842147193357.589291887
2021028.74573219193300.3417746132021891.86214649193216.672326289
#Sta/Elev= 30
       0 1504.11   124.4    1504   228.8 1509.19   288.8 1508.35   344.1 1504.37
   411.7 1496.05   434.5 1490.77   484.2 1482.98   520.4 1482.15   543.5 1479.07
   569.8 1478.47     583 1474.86   599.5 1474.68   652.2 1474.87     662 1478.59
   737.6 1487.86   823.4 1494.62  1014.5 1503.63  1060.3 1504.42  1248.5 1515.29
  1377.1 1519.61  1413.3 1522.29  1466.6 1522.99  1485.8 1527.07  1518.8 1530.27
  1657.2 1536.11  1729.8 1545.78  1749.5 1546.66  1808.9 1557.36  1863.5 1569.36
#Mann= 13 ,-1 , 0
       0     .05       0      50      .1       0      90     .05       0
     210    .035       0     220     .05       0  436.52      .1       0
  536.52     .12       0   569.8    .045       0     662     .12       0
  736.52      .1       0  826.52    .035       0 1716.38     .06       0
 1816.38      .1       0
Bank Sta=569.8,662
XS Rating Curve= 0 ,0
Exp/Cntr(USF)=0,0
Exp/Cntr=0.3,0.1

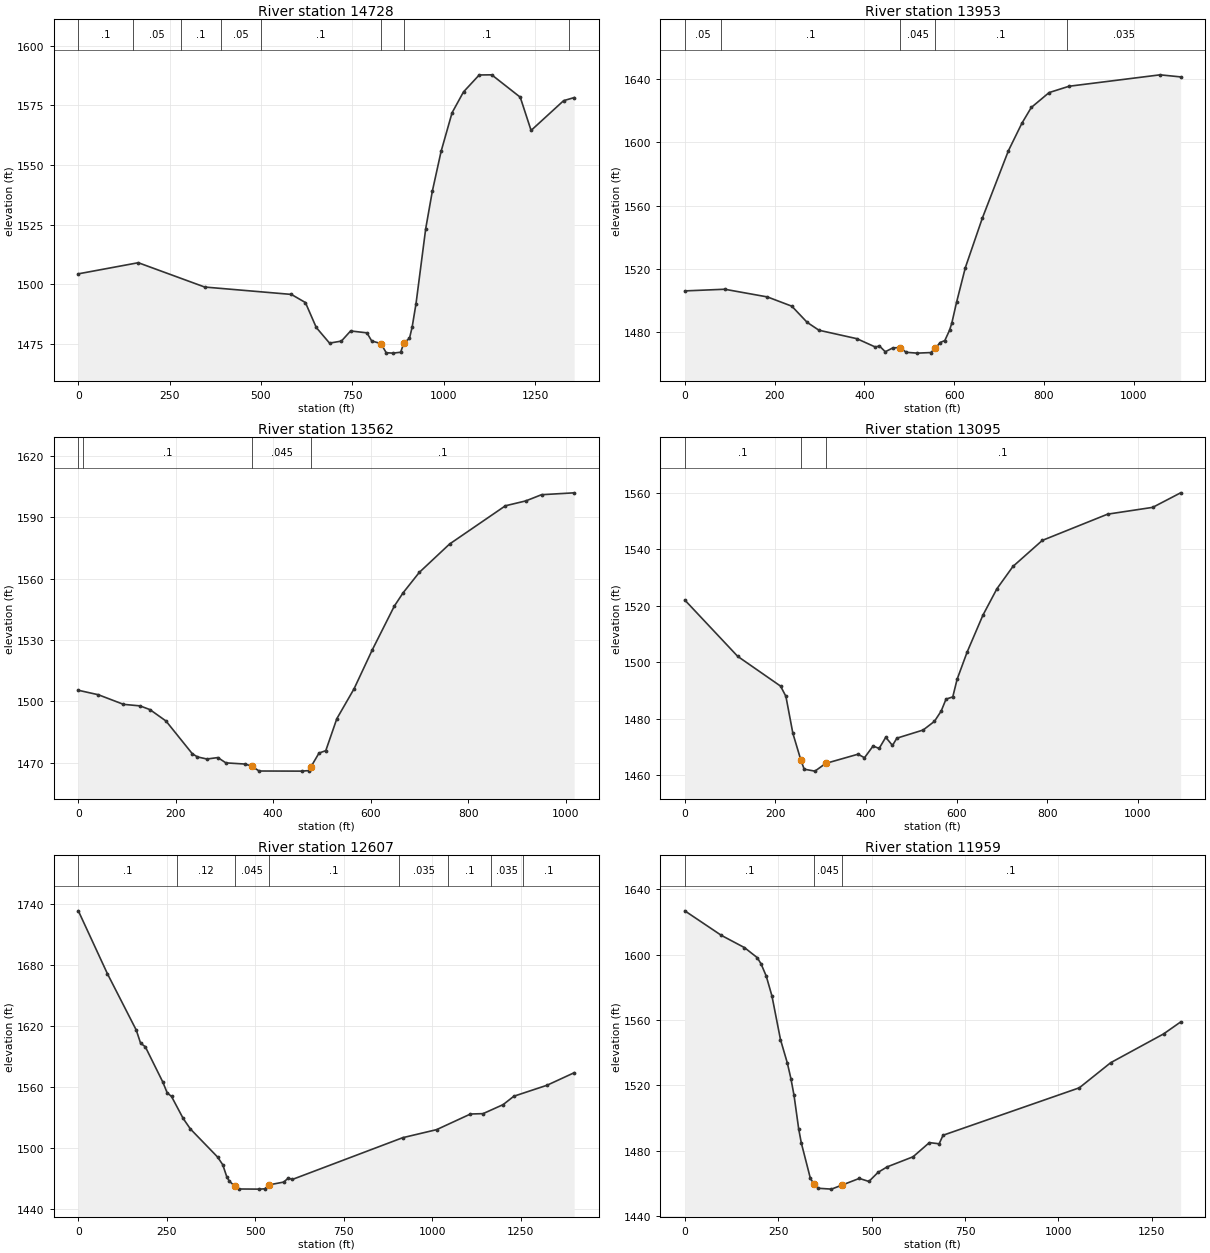
Type RM Length L Ch R = 1 ,14728   ,733.1,775.6,833.8
XS GIS Cut Line= 4
2020103.48885043193234.286946988 2020359.3901456 193714.28536106
2020566.36193882194167.8618440812020601.59118022194480.521361503
#Sta/Elev= 30
       0 1504.37   164.1 1509.03   345.9 1498.84   583.1 1495.75   621.6 1492.34
   651.3 1481.89   687.6 1475.35   720.1 1476.19   745.3 1480.44     790 1479.65
     803 1476.25   828.3 1475.15   842.7 1471.33   860.7 1471.15   882.4 1471.52
   891.1 1475.54   906.4 1477.31   913.8 1482.11   924.3 1491.84   950.9 1523.33
   968.9 1538.92     993 1555.69    1023 1571.86  1054.3 1580.59  1097.3 1587.69
  1131.6 1587.75  1209.6 1578.38  1239.3 1564.45  1328.4 1576.93  1357.2 1578.21
#Mann= 8 ,-1 , 0
       0      .1       0     150     .05       0     280      .1       0
     390     .05       0     500      .1       0   828.3    .045       0
   891.1      .1       0 1342.52     .04       0
Bank Sta=828.3,891.1
XS Rating Curve= 0 ,0
Exp/Cntr(USF)=0,0
Exp/Cntr=0.3,0.1

Type RM Length L Ch R = 1 ,13953   ,393.5,390.6,389.6
XS GIS Cut Line= 4
2020069.72749409193227.9261117362020074.62044428193438.322970095
2019722.32803029193873.7955373972019511.93117193194133.121897701
#Sta/Elev= 30
       0 1506.16    88.9 1507.21   184.1 1502.36   238.4 1496.53   272.6 1486.32
   298.9 1481.36   383.3 1476.04   424.3  1470.8   433.6 1471.44   446.6 1467.79
   463.5 1470.24   480.1 1470.43     493 1467.45   517.6 1466.93   547.7 1467.28
   558.4 1470.07   568.8 1473.61   579.2 1474.85   589.7 1481.32   594.9 1485.99
   605.3  1498.9   624.9 1520.81   662.7 1551.97   720.9 1594.57   750.8 1611.82
   771.8 1621.82   811.5 1631.21     856 1635.21  1058.8 1642.41  1104.5  1641.1
#Mann= 5 ,-1 , 0
       0     .05       0      80      .1       0   480.1    .045       0
   558.4      .1       0  850.58    .035       0
Bank Sta=480.1,558.4
XS Rating Curve= 0 ,0
Exp/Cntr(USF)=0,0
Exp/Cntr=0.3,0.1

Type RM Length L Ch R = 1 ,13562   ,453.9,467.5,469.5
XS GIS Cut Line= 4
 2019976.7614404193081.1376059042019864.22358593193134.960058042
2019511.93117193  193521.50312342019286.85546299193815.080135064
#Sta/Elev= 30
       0 1505.38    41.1 1503.19    92.7 1498.49   126.6 1497.74     147 1495.91
   179.9 1490.34   233.9 1474.32   244.4 1472.76   263.9 1471.72   286.4 1472.43
   302.8 1469.84     343 1469.24     357 1468.07     371 1465.85   458.7 1465.79
   472.9 1466.05   477.7    1468     494 1474.63   507.9 1475.81   530.6 1491.48
     566 1506.13   603.1 1525.05   648.7 1546.64   666.8 1553.17   699.8 1563.09
     762 1576.99   876.6 1595.72   918.4  1598.1   950.7 1601.14  1017.7 1602.06
#Mann= 4 ,-1 , 0
       0     .05       0      10      .1       0     357    .045       0
   477.7      .1       0
Bank Sta=357,477.7
XS Rating Curve= 0 ,0
Exp/Cntr(USF)=0,0
Exp/Cntr=0.3,0.1

Type RM Length L Ch R = 1 ,13095   ,492.1,487.9,481
XS GIS Cut Line= 4
2019650.08150643192726.912174546 2019565.5119969192823.563042584
2019239.31531727193337.0207790332019106.42037372193669.258137913
#Sta/Elev= 30
       0 1522.06   116.8 1502.13   211.4  1491.6   223.2 1487.97   238.6 1474.88
   256.4 1465.33   263.6 1462.19   287.3 1461.51   311.1 1464.24   382.4  1467.5
   396.7 1466.25   415.7 1470.41     429 1469.53   443.6 1473.49   458.5 1470.59
   468.1 1473.17   526.2 1476.06   551.2 1479.14     566 1482.77   576.7 1486.99
   591.6 1487.78   601.1 1493.99   623.4 1503.69   658.1 1516.69     689 1526.04
   724.4 1533.94   789.2 1543.16   933.4 1552.45    1033 1554.86  1094.6    1560
#Mann= 3 ,-1 , 0
       0      .1       0   256.4    .045       0   311.1      .1       0
Bank Sta=256.4,311.1
XS Rating Curve= 0 ,0
Exp/Cntr(USF)=0,0
Exp/Cntr=0.3,0.1

Type RM Length L Ch R = 1 ,12607   ,656.3,648.3,635
XS GIS Cut Line= 4
2019354.08822306192279.9019098722019148.70512848192551.732476228
2018913.11863764192998.7427409022018701.69486381193512.200477352
#Sta/Elev= 30
       0 1733.57      82 1671.87   163.7 1616.31   175.9 1603.48   189.3 1599.92
   238.7 1565.26     251 1554.71   263.4 1551.03   296.2 1529.49   316.8 1519.06
   393.4 1491.57   408.2 1483.91   419.3 1472.32   426.7  1467.8   441.5 1463.06
   452.7 1460.08     512 1459.94   526.9 1460.25     539 1464.14   580.3 1466.86
   593.6 1470.87   604.7 1469.44   916.7 1510.51  1012.5 1518.42  1108.3  1533.8
  1143.8 1534.15  1200.6 1543.04  1230.9 1551.28  1324.8  1562.1  1401.3 1574.38
#Mann= 8 ,-1 , 0
       0      .1       0     280     .12       0   441.5    .045       0
     539      .1       0  905.99    .035       0 1045.99      .1       0
 1165.99    .035       0 1255.99      .1       0
Bank Sta=441.5,539
XS Rating Curve= 0 ,0
Exp/Cntr(USF)=0,0
Exp/Cntr=0.3,0.1

Type RM Length L Ch R = 1 ,11959   ,794.1,770.6,733.5
XS GIS Cut Line= 4
2018623.16603353192032.2340605262018556.71856175 192249.69851361
2018357.37614643192811.4816840792018309.05071241193312.858062024
#Sta/Elev= 30
       0  1626.7    97.9  1611.7   159.8 1604.21   193.9 1598.09   204.2 1594.24
     218 1586.82   233.3 1574.63   256.1 1548.02   274.4 1533.73     284  1524.2
   292.4 1513.89   304.8  1493.5   311.8 1484.88   336.2 1463.11   346.6 1459.51
   357.1 1457.12   392.6 1456.59   419.7 1458.96   467.1 1463.14   492.8 1461.28
   517.2 1466.83   541.5 1470.18     611 1476.36   654.7 1485.03   680.8  1484.3
   691.3 1489.52    1056 1518.52    1140 1533.87  1281.7 1551.48  1327.2 1558.77
#Mann= 3 ,-1 , 0
       0      .1       0   346.6    .045       0   419.7      .1       0
Bank Sta=346.6,419.7
XS Rating Curve= 0 ,0
Exp/Cntr(USF)=0,0
Exp/Cntr=0.3,0.1

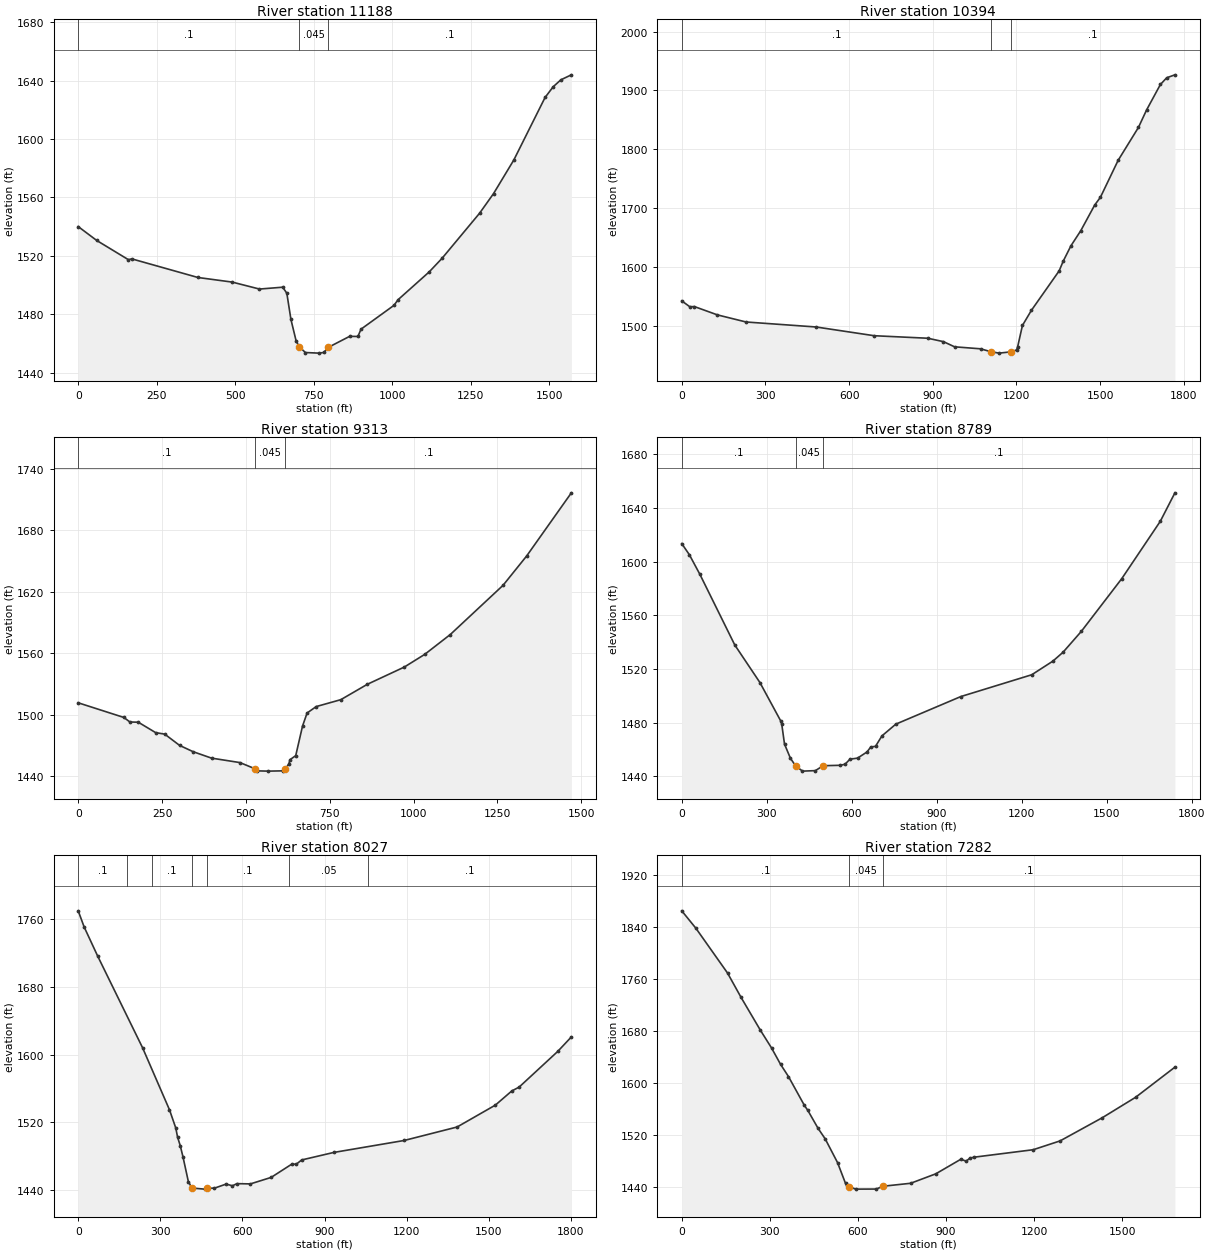
Type RM Length L Ch R = 1 ,11188   ,651,793.8,928
XS GIS Cut Line= 4
 2018296.9693539192026.1933812732017741.22686269192183.251041834
2017753.30822119192654.4240235182017439.19290007 193071.23089193
#Sta/Elev= 30
       0    1540    59.1 1530.47   159.8 1517.33   170.8 1517.87   381.4 1505.12
   490.5 1501.97   577.4  1497.2   651.4 1498.47   664.5 1494.34   677.6 1476.35
     694 1461.77   703.9 1457.74   723.6 1453.72   766.4 1453.31   782.6 1453.76
   795.8 1457.17   864.7 1464.82   890.9 1464.71   900.8 1469.72  1005.8 1486.05
  1018.9 1489.92  1118.2    1509  1159.1 1518.31  1278.5 1549.16    1323 1562.62
  1387.7 1585.69    1487 1628.44    1513  1635.8  1537.3 1640.53  1570.8 1643.95
#Mann= 3 ,-1 , 0
       0      .1       0   703.9    .045       0   795.8      .1       0
Bank Sta=703.9,795.8
XS Rating Curve= 0 ,0
Exp/Cntr(USF)=0,0
Exp/Cntr=0.3,0.1

Type RM Length L Ch R = 1 ,10394   ,980.2,1081.2,1153.7
XS GIS Cut Line= 4
2018339.25410867191941.623871741 2017511.6810511 192044.31541903
2016998.22331465 191965.78658875 2016611.6198425191814.769607441
#Sta/Elev= 30
       0 1542.19    28.9 1532.14    45.5 1532.43   128.1 1518.29   230.6 1506.25
   481.9 1497.75   690.1 1482.91   882.1 1478.64   938.5 1472.81   978.3 1464.06
  1071.3 1460.66  1109.3 1455.64  1138.1 1453.32  1181.3 1455.54  1200.7 1458.74
    1204  1463.1  1221.6 1500.34  1253.8 1526.08  1353.4 1593.23  1367.5 1609.31
  1395.6 1635.83  1430.9 1661.51  1480.5 1704.85  1501.3 1718.31  1564.7 1780.98
  1637.6 1837.01  1666.8  1866.7  1716.3 1909.97  1738.9  1921.4  1768.4  1926.4
#Mann= 3 ,-1 , 0
       0      .1       0  1109.3    .045       0  1181.3      .1       0
Bank Sta=1109.3,1181.3
XS Rating Curve= 0 ,0
Exp/Cntr(USF)=0,0
Exp/Cntr=0.3,0.1

Type RM Length L Ch R = 1 ,9313    ,542.3,524.3,490.7
XS GIS Cut Line= 4
2018200.31848587191893.2984377222018049.30150456191778.525531927
2017898.28452325191210.7016822062017300.25727727 190860.34228557
#Sta/Elev= 30
       0 1511.61   136.2  1497.3   154.1  1492.9   179.2 1492.66   230.9 1482.51
     258 1481.03   302.2 1470.06   342.9 1463.86   397.5 1457.63   482.1 1453.28
   526.2 1447.38   526.2 1447.37   534.3 1445.18     567 1444.94   611.1 1445.22
   617.9 1446.99   628.1 1452.13   631.5 1456.12   648.5 1460.04   668.8  1488.9
   682.4 1501.65   709.6 1507.93     783 1514.67   862.1 1529.68   972.4 1546.51
  1033.3 1558.91  1109.4 1578.24  1266.5  1626.2  1336.9 1654.83  1470.3 1716.48
#Mann= 3 ,-1 , 0
       0      .1       0   526.2    .045       0   617.9      .1       0
Bank Sta=526.2,617.9
XS Rating Curve= 0 ,0
Exp/Cntr(USF)=0,0
Exp/Cntr=0.3,0.1

Type RM Length L Ch R = 1 ,8789    ,810.9,762.2,677.5
XS GIS Cut Line= 4
2018701.69486381191699.9967016462018580.88127876191476.491569309
2018151.99305185190969.074512112 2017396.9081453190642.877832485
#Sta/Elev= 30
       0 1613.38    26.9 1605.07      64 1590.47   187.2 1537.82   275.9 1509.85
   348.9 1481.41     353 1478.83   362.8 1463.94   383.8 1453.33   401.8 1447.81
   426.2 1443.81   471.7 1444.18   499.3 1447.84   560.2 1448.16   576.6 1448.98
   593.8  1452.7   620.7 1453.51   653.9 1458.08   667.2 1461.78     684 1462.29
   706.8 1470.09   755.7 1478.82   985.2 1499.38  1235.6 1515.63  1310.2 1525.78
  1346.2 1532.44  1410.5 1547.93  1553.5  1587.3  1689.3 1629.97    1741  1651.2
#Mann= 3 ,-1 , 0
       0      .1       0   401.8    .045       0   499.3      .1       0
Bank Sta=401.8,499.3
XS Rating Curve= 0 ,0
Exp/Cntr(USF)=0,0
Exp/Cntr=0.3,0.1

Type RM Length L Ch R = 1 ,8027    ,775.6,745,697.4
XS GIS Cut Line= 4
2019257.43735503190697.2439457562018997.68814718190691.203266504
2018339.25410867190727.4473420182017469.39629633190576.430360709
#Sta/Elev= 30
       0 1770.17    21.7 1751.09    70.9 1716.82   235.4 1608.11   333.6 1534.85
   356.6  1513.3   363.1 1502.56     373 1492.37   382.9 1479.18   402.6 1449.86
   415.7 1442.35   461.7 1441.06   471.6 1442.15   497.9 1442.21   540.6 1447.03
   563.6 1445.02     580 1447.54   629.3 1447.24   704.9  1454.9   780.4  1470.6
   796.9 1470.54   816.6 1475.56   933.9 1484.45  1191.5 1498.62  1384.6 1514.53
  1524.5 1540.45  1584.4 1557.17    1611 1561.66  1752.1 1603.86  1802.1 1621.06
#Mann= 7 ,-1 , 0
       0      .1       0     180     .12       0  269.82      .1       0
   415.7    .045       0   471.6      .1       0  769.82     .05       0
 1059.25      .1       0
Bank Sta=415.7,471.6
XS Rating Curve= 0 ,0
Exp/Cntr(USF)=0,0
Exp/Cntr=0.3,0.1

Type RM Length L Ch R = 1 ,7282    ,1038.5,1047.9,1031.9
XS GIS Cut Line= 4
2018955.40339241189736.7759446332018629.20671278 189936.11835996
2018145.95237259 190244.193001832017469.39629633190503.942209681
#Sta/Elev= 30
       0 1864.69    48.3 1837.78   155.9 1768.94   202.2 1731.26   267.4 1681.18
   305.9 1653.47   336.6 1628.28   363.6 1609.42   417.8 1565.01   429.5 1557.32
   464.4 1529.68   488.7 1513.45   530.6 1477.06   557.9 1444.91   561.8 1442.02
   569.6 1439.76   592.7 1436.06   662.9 1436.18   685.4  1440.5   779.7 1445.06
   865.3 1459.59   950.8 1482.08   968.9 1479.13   981.7 1483.81   996.9 1485.31
  1197.3 1496.75    1289 1510.36  1432.8 1546.07  1546.1 1577.48  1680.1 1623.94
#Mann= 3 ,-1 , 0
       0      .1       0   569.6    .045       0   685.4      .1       0
Bank Sta=569.6,685.4
XS Rating Curve= 0 ,0
Exp/Cntr(USF)=0,0
Exp/Cntr=0.3,0.1

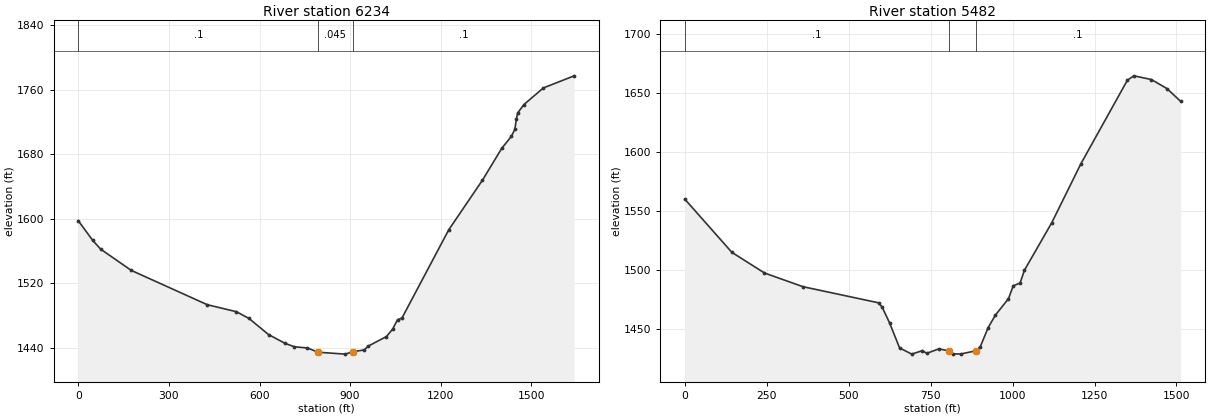
Type RM Length L Ch R = 1 ,6234    ,760.7,751.5,745.4
XS GIS Cut Line= 4
2018454.02701446188897.1215285562017952.65063652189174.992774164
2017408.98950381189573.6776048192017106.95554119189827.386133418
#Sta/Elev= 30
       0 1597.45    47.8 1573.08      74 1562.29   175.3 1535.97   426.8 1493.46
   523.4 1484.75   565.4 1476.35   629.8 1456.46   684.3 1445.58   715.3 1441.28
   758.7  1439.8   794.3 1434.53   883.9 1432.18   908.4  1435.1   947.2 1437.43
   959.4 1441.97  1020.4 1454.03  1040.8 1463.16    1057 1474.81  1071.6 1476.86
  1226.5 1586.22  1338.3 1647.84  1402.5 1687.51    1434 1702.04  1445.4  1710.7
  1450.9 1724.22  1454.9 1731.21  1475.4 1741.45  1539.7 1762.09  1641.9 1777.14
#Mann= 3 ,-1 , 0
       0      .1       0   794.3    .045       0   908.4      .1       0
Bank Sta=794.3,908.4
XS Rating Curve= 0 ,0
Exp/Cntr(USF)=0,0
Exp/Cntr=0.3,0.1

Type RM Length L Ch R = 1 ,5482    ,568,571.1,575.4
XS GIS Cut Line= 4
2017886.20316474188268.8908863122017469.39629633188564.884169677
2016961.97923913189023.9757928552016720.35206904189229.358887435
#Sta/Elev= 30
       0 1560.17   143.5 1515.21     243 1497.74   360.6 1486.15   591.3 1472.52
   601.8 1469.02   624.6 1455.63   655.2  1434.4   692.4 1429.15   724.9 1432.14
     738 1429.81     775 1433.61   806.2 1431.89   817.8 1429.35   841.4 1429.25
   887.5 1431.92   901.5 1435.42   925.4 1451.54   947.5  1462.1   987.4 1476.02
  1002.1 1486.95  1022.8 1489.23  1036.3 1500.17  1119.5 1540.23  1208.2    1590
  1350.3 1660.76    1370  1664.4  1423.5 1661.26  1470.9 1653.63  1512.6 1642.85
#Mann= 3 ,-1 , 0
       0      .1       0   806.2    .045       0   887.5      .1       0
Bank Sta=806.2,887.5
XS Rating Curve= 0 ,0
Exp/Cntr(USF)=0,0
Exp/Cntr=0.3,0.1