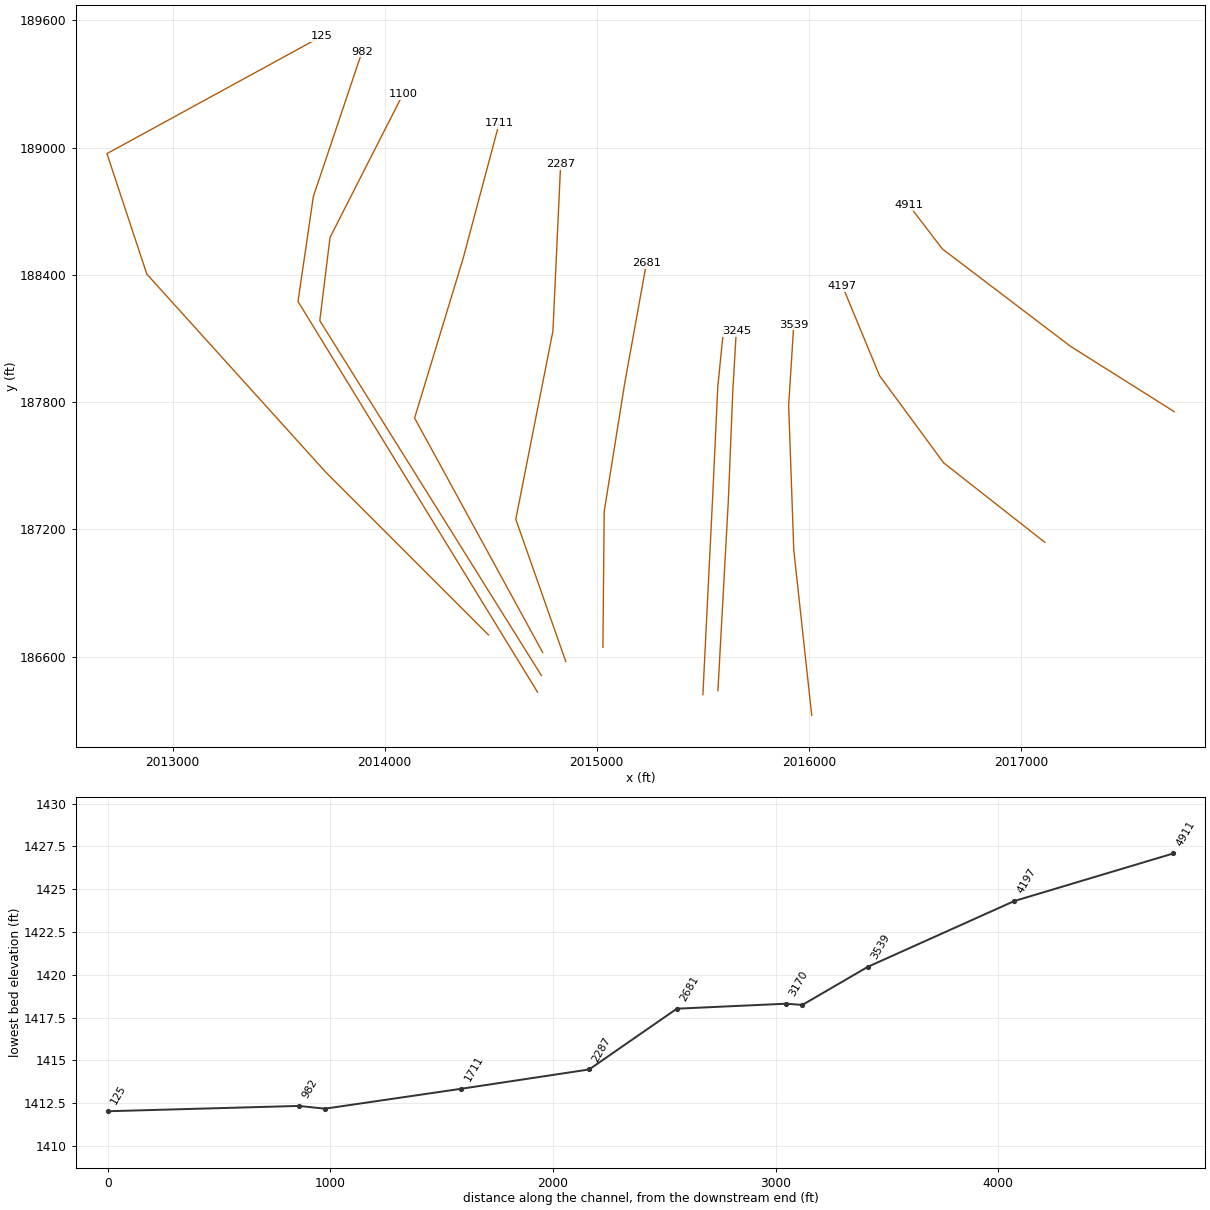
HEC-RAS study INDIANCK.prj: INDIANCK

--- INDIANCK.g01 (geometry) --- (continued)

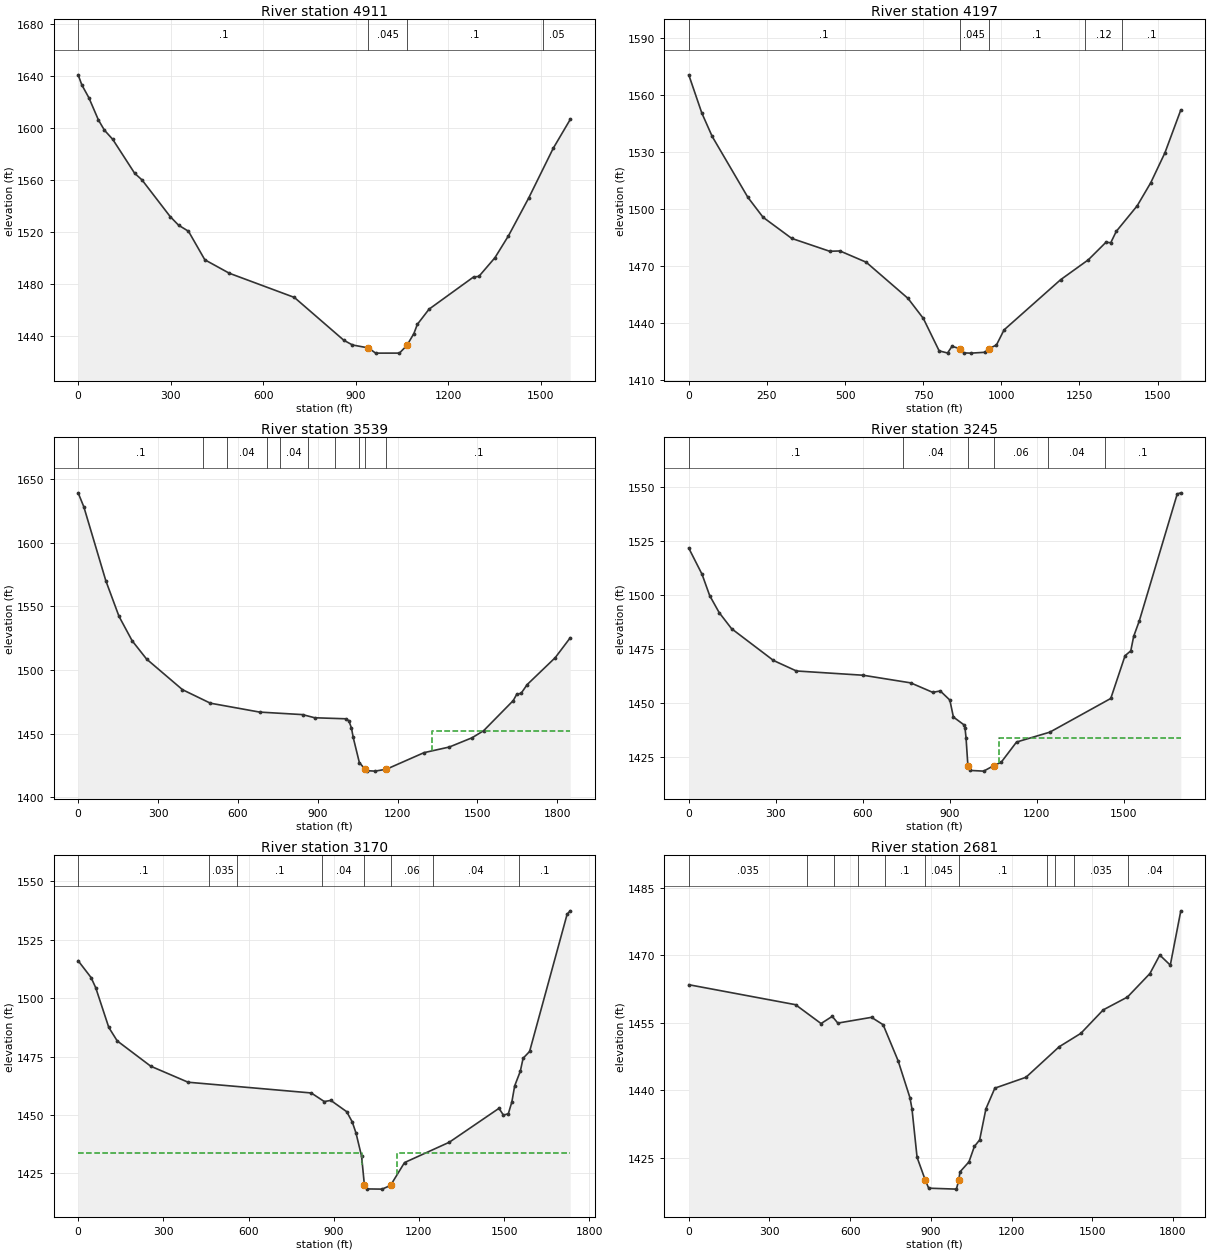
Type RM Length L Ch R = 1 ,4911    ,733.6,714.4,692.8
XS GIS Cut Line= 4
2017723.10482493187755.4331498622017233.80980549188063.507791732
2016629.74188025 188522.599414912016472.68421969 188727.98250949
#Sta/Elev= 30
       0 1640.97      12 1633.18    34.7 1623.41    65.7 1606.31    85.1 1598.46
   112.2 1591.37   183.3 1565.29   207.1  1560.2   298.3 1532.07   325.5 1525.44
   357.8 1520.74   410.8 1498.82   490.2 1488.48   701.1  1469.9   861.5 1436.97
   889.6 1433.35   941.2  1431.1   964.6 1427.09  1041.8 1427.11 1065.891432.981
  1088.7 1442.15  1099.8 1449.18  1137.8 1460.87  1282.1  1485.6  1299.4 1486.04
  1351.5 1500.44  1395.4 1517.28  1460.9 1546.29  1540.5 1584.52  1595.5 1606.64
#Mann= 4 ,-1 , 0
       0      .1       0   941.2    .045       0 1065.89      .1       0
 1506.93     .05       0
Bank Sta=941.2,1065.89
XS Rating Curve= 0 ,0
Exp/Cntr(USF)=0,0
Exp/Cntr=0.3,0.1

Type RM Length L Ch R = 1 ,4197    ,694.5,657.6,587.6
XS GIS Cut Line= 4
2017112.99622044187139.2838661222016635.78255951187513.805979768
2016333.74859689187924.5721689282016158.56889857188347.419716592
#Sta/Elev= 30
       0 1570.61    41.8 1550.51      75 1538.21     189 1506.24   237.7 1495.73
   329.4 1484.62   450.7 1477.86   483.7 1478.02   567.6 1472.11   701.2 1453.12
   750.5 1442.54   801.1  1425.5   827.9 1424.38   842.2 1427.89   866.3 1426.72
   879.5 1424.43     903 1424.31   947.7 1424.75  960.82 1426.73   984.3 1428.56
  1008.8 1436.53  1189.5 1462.89  1278.3 1473.37  1334.8  1482.6  1350.1 1482.35
  1367.6 1488.29  1434.5 1501.72  1478.1 1513.91  1523.3 1529.59  1574.2 1552.15
#Mann= 5 ,-1 , 0
       0      .1       0   866.3    .045       0  960.82      .1       0
 1266.49     .12       0 1386.49      .1       0
Bank Sta=866.3,960.82
XS Rating Curve= 0 ,0
Exp/Cntr(USF)=0,0
Exp/Cntr=0.3,0.1

Type RM Length L Ch R = 1 ,3539    ,299.5,294.6,290.7
XS GIS Cut Line= 4
2016013.59259651186323.7921670552015929.02308698187103.039790608
2015904.86036997187785.6365461242015929.02308698188166.199339022
#Sta/Elev= 30
       0 1639.11    21.4 1628.09   103.9  1570.1   153.4  1542.1   202.9 1522.86
   257.1 1508.51   391.9 1484.46   496.6 1473.85   681.4 1466.86   842.8 1464.87
   888.7 1462.39  1006.9 1461.58  1016.8    1460  1026.6 1454.34  1033.2 1446.92
  1056.2 1427.24  1075.9 1422.39  1085.7  1420.8  1115.2 1420.47  1157.9 1421.97
  1299.1 1434.98  1394.3 1439.42  1479.9 1446.71    1523 1452.22  1634.2 1475.88
  1647.3 1480.79  1663.8 1481.62  1686.8  1488.5    1792 1509.62  1848.2 1525.19
#Mann= 10 ,-1 , 0
       0      .1       0     470     .06       0     560     .04       0
     710      .1       0     760     .04       0  863.82      .1       0
  963.82     .04       0 1053.82      .1       0  1075.9    .045       0
  1157.9      .1       0
#XS Ineff= 2 , 0
                         1329.51         1452.08
Permanent Ineff=
       F       F
Bank Sta=1075.9,1157.9
XS Rating Curve= 0 ,0
Exp/Cntr(USF)=0,0
Exp/Cntr=0.5,0.3

Type RM Length L Ch R = 1 ,3245    ,76.9,74.8,84
XS GIS Cut Line= 4
2015571.31258673186440.3090629192015620.45852784187336.637417387
2015641.52107403187853.839940462 2015657.9030544188134.673889643
#Sta/Elev= 30
       0 1521.57    45.9 1509.42    72.1 1499.58     105 1491.67   147.7 1484.23
   292.1 1469.51   371.1 1464.65   601.2 1462.67   765.4 1459.13     841 1454.75
   867.3 1455.38   900.2 1451.16   912.5  1443.3   949.4 1439.64   952.7 1438.01
     956  1433.8   962.5 1420.69   969.1 1418.57  1016.8 1418.24  1051.3 1420.75
  1077.5 1422.39  1130.2 1431.72  1244.9 1436.29  1455.1 1451.91  1504.4 1471.73
  1524.1 1473.97    1534 1480.66  1553.5 1487.87  1684.3 1546.68  1696.6 1547.19
#Mann= 6 ,-1 , 0
       0      .1       0     740     .04       0   962.5    .045       0
  1051.3     .06       0 1237.67     .04       0 1435.31      .1       0
#XS Ineff= 2 , 0
             950 1433.69    1068         1433.69
Permanent Ineff=
       F       F
Bank Sta=962.5,1051.3
XS Rating Curve= 0 ,0
Exp/Cntr(USF)=0,0
Exp/Cntr=0.5,0.3

Type RM Length L Ch R = 1 ,3170    ,488.7,489.1,473.7
XS GIS Cut Line= 4
2015500.42541739186420.9525829722015547.23107559187368.767161457
2015570.63390469187871.9279870722015598.71729961188150.421653343
#Sta/Elev= 30
       01515.992  45.5151508.801  61.9391504.426 107.9261487.465  137.491481.718
 255.7441470.873 387.1371464.031 820.7351459.438 866.7221455.766 889.7161456.259
 945.5581451.435 965.2651447.029 978.4031442.271 998.1091432.3161007.9621420.034
1018.7031418.3961070.365 1418.311099.9251419.891 1149.191429.6621306.8411438.363
1481.7971452.8641497.5131449.9561514.7471450.558 1527.19 1455.621537.0821462.467
1556.8671468.714 1566.761474.2761589.6321477.1951721.7411535.871 1732.581537.333
#Mann= 8 ,-1 , 0
       0      .1       0     460    .035       0     560      .1       0
     860     .04       01007.962    .045       01099.925     .06       0
 1248.97     .04       0 1552.67      .1       0
#XS Ineff= 2 , 0
            1001 1433.69    1122         1433.69
Permanent Ineff=
       F       F
Bank Sta=1007.962,1099.925
XS Rating Curve= 0 ,0
Exp/Cntr(USF)=0,0
Exp/Cntr=0.5,0.3

Type RM Length L Ch R = 1 ,2681    ,405.1,393.9,393.5
XS GIS Cut Line= 4
2015028.96187838186643.9481674292015035.00255763187284.260168178
2015131.65342567187888.3280934132015234.34497296188456.151943134
#Sta/Elev= 30
       0 1463.45   396.9 1459.01   491.8 1454.82   533.4 1456.42   554.1 1454.92
   679.3  1456.2   722.5 1454.56   778.1 1446.57   822.1 1438.36   829.7  1435.9
   848.7 1425.09     879 1420.06   891.9 1418.23   994.9 1418.02 1003.74 1420.05
  1008.2 1421.85  1041.6 1424.08  1061.7  1427.5  1081.3 1428.96  1104.7 1435.88
  1137.8 1440.46  1253.6 1442.88  1376.9 1449.66  1457.5 1452.64  1540.8 1457.86
  1630.8 1460.71  1714.2 1465.93  1750.9 1470.04    1790  1467.8  1829.1 1479.87
#Mann= 11 ,-1 , 0
       0    .035       0     440     .06       0     540     .04       0
     630    .035       0  730.34      .1       0     879    .045       0
 1003.74      .1       0 1332.09     .05       0 1362.09      .1       0
 1432.09    .035       0 1632.09     .04       0
Bank Sta=879,1003.74
XS Rating Curve= 0 ,0
Exp/Cntr(USF)=0,0
Exp/Cntr=0.3,0.1

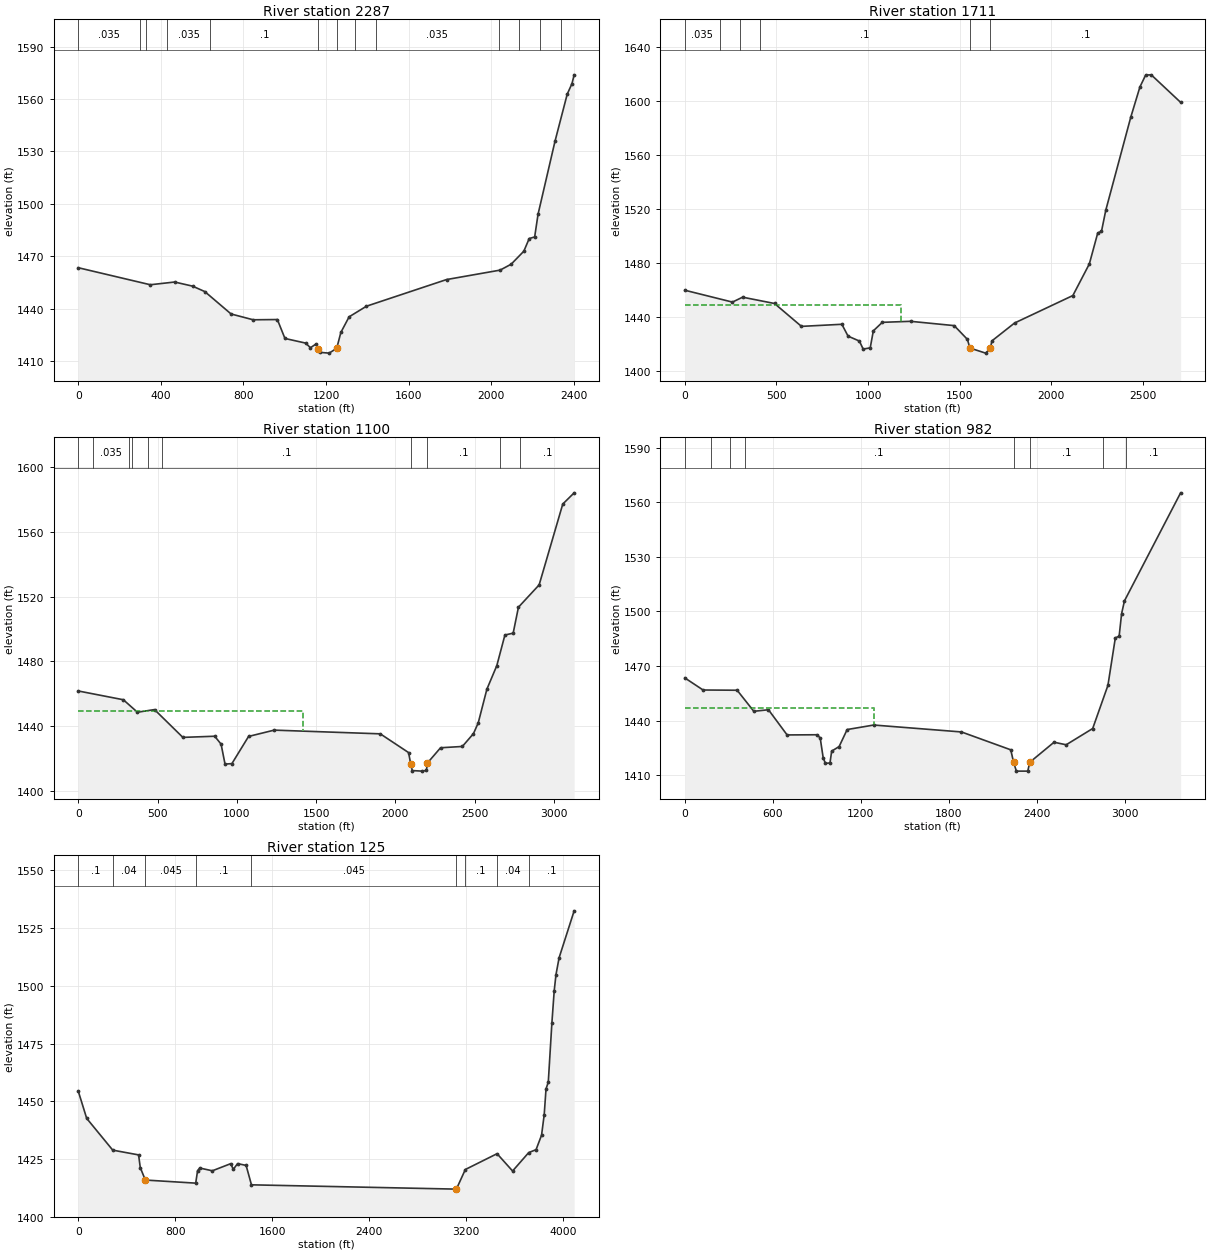
Type RM Length L Ch R = 1 ,2287    ,580.4,575.9,580.2
XS GIS Cut Line= 4
2014853.78218006186577.5006956532014618.19568922187248.016092664
2014793.37538754 188135.995942762014829.61946305188921.284245565
#Sta/Elev= 30
       0 1463.36   348.7 1453.62   466.5 1455.18   553.4 1452.82   612.5 1449.72
     740 1436.88     847 1433.56   964.1  1433.7  1000.9 1422.87  1101.2 1420.21
  1124.5 1417.56  1151.3 1419.69    1162 1417.11  1171.4  1414.9  1214.9 1414.47
  1251.7 1417.22  1271.7 1426.31  1311.7 1435.25  1395.5 1441.32  1783.7 1456.59
    2043 1461.99  2096.6 1465.37  2158.1 1472.83  2184.2 1480.08  2210.6 1480.98
    2227 1493.99  2309.1 1535.78  2368.3 1562.74  2391.3 1568.76  2401.9 1573.81
#Mann= 13 ,-1 , 0
       0    .035       0     300     .06       0     330     .04       0
     430    .035       0     640      .1       0    1162    .045       0
  1251.7      .1       0  1340.7     .05       0  1440.7    .035       0
 2035.79      .1       0 2135.79     .04       0 2235.79      .1       0
 2335.79     .08       0
Bank Sta=1162,1251.7
XS Rating Curve= 0 ,0
Exp/Cntr(USF)=0,0
Exp/Cntr=0.3,0.1

Type RM Length L Ch R = 1 ,1711    ,593.4,610.7,634.2
XS GIS Cut Line= 4
2014745.04995352 186619.785450422014140.98202829  187725.2297536
2014370.52783987188480.3146601442014539.66685894189114.585981641
#Sta/Elev= 30
       0 1459.97   259.9 1451.17   315.5 1454.81   489.5 1450.13   636.5 1433.17
     857 1434.72   890.9 1425.92   952.6 1422.29   973.2 1416.35  1011.7 1417.23
  1028.7 1429.87  1077.7 1436.17  1231.7 1436.92    1470 1433.73    1542 1423.53
  1555.7 1417.09  1641.4 1413.34 1667.21 1416.91  1675.7 1422.41  1799.3 1435.66
  2117.4 1456.03  2207.3 1479.46  2253.2 1502.43  2273.6 1503.59  2297.3 1519.41
  2433.2 1588.15  2483.4 1610.69  2514.7 1619.48  2545.1 1619.64  2705.4 1599.24
#Mann= 6 ,-1 , 0
       0    .035       0     190     .04       0     300    .035       0
     410      .1       0  1555.7    .045       0 1667.21      .1       0
#XS Ineff= 2 , 0
         1177.65 1448.79
Permanent Ineff=
       F       F
Bank Sta=1555.7,1667.21
XS Rating Curve= 0 ,0
Exp/Cntr(USF)=0,0
Exp/Cntr=0.3,0.1

Type RM Length L Ch R = 1 ,1100    ,115.2,118.1,123.4
XS GIS Cut Line= 4
2014739.00927427186511.0532238782013693.97176361188184.321376779
2013742.29719763188576.9655281812014086.61591501189253.521604445
#Sta/Elev= 30
       0 1461.67   283.9 1456.26   372.9 1448.54   480.5 1450.19   659.3 1433.02
   860.2 1433.73   900.5 1428.83   925.3 1416.53   968.6 1416.81  1073.9 1433.61
  1235.3  1437.5  1904.6 1435.21  2083.1 1423.63  2096.4 1416.68  2106.3 1412.52
  2169.1 1412.18  2195.1  1412.6  2202.1  1417.2  2284.8 1426.61  2422.3 1427.41
  2492.5 1435.37  2522.4 1441.97  2577.1 1462.81  2639.5  1477.3  2690.7 1496.23
  2742.8  1497.4  2776.1 1513.42  2906.6  1527.2  3055.7 1577.13  3127.5 1584.05
#Mann= 10 ,-1 , 0
       0      .1       0      90    .035       0     320     .04       0
     340      .1       0     440    .035       0     530      .1       0
  2096.4    .045       0  2202.1      .1       0  2658.4     .04       0
  2788.4      .1       0
#XS Ineff= 2 , 0
         1419.05 1449.12
Permanent Ineff=
       F       F
Bank Sta=2096.4,2202.1
XS Rating Curve= 0 ,0
Exp/Cntr(USF)=0,0
Exp/Cntr=0.3,0.1

Type RM Length L Ch R = 1 ,982     ,643.2,857.5,915.2
XS GIS Cut Line= 4
2014720.88723651186432.5243935972013591.28021632188274.931565564
2013663.76836735188770.2672642572013893.31417894189452.864019772
#Sta/Elev= 30
       0 1463.53   124.7 1456.88     357 1456.75   470.8 1445.19   570.7 1446.04
   697.8 1432.21   903.1 1432.31   923.7 1430.49   944.1 1419.55   959.5 1416.59
   990.3 1416.84  1001.8 1423.33  1052.6 1425.82  1107.4 1435.17  1288.8 1437.65
    1887 1433.85  2223.3 1424.04 2242.44 1417.24  2261.6 1412.34  2339.4 1412.34
  2352.7 1417.18  2518.4  1428.2  2601.4 1426.81  2782.1 1435.73    2886  1459.4
  2936.6  1485.5  2962.5 1486.42  2979.4 1498.84  2998.8 1505.82  3381.9 1565.14
#Mann= 8 ,-1 , 0
       0      .1       0     180    .035       0     310     .04       0
     410      .1       0 2242.44    .045       0  2352.7      .1       0
 2851.74     .04       0 3011.74      .1       0
#XS Ineff= 2 , 0
          1293.7 1446.97
Permanent Ineff=
       F       F
Bank Sta=2242.44,2352.7
XS Rating Curve= 0 ,0
Exp/Cntr(USF)=0,0
Exp/Cntr=0.3,0.1

Type RM Length L Ch R = 1 ,125     ,,,
XS GIS Cut Line= 5
2014489.10682264186703.0847437652013721.01481558187471.176750827
2012878.46490987188403.8599022582012690.36074488188972.091234013
2013701.42063172189524.647218685
#Sta/Elev= 30
       0 1454.32      69 1442.64   284.1  1428.9   497.5 1426.84   511.4 1421.35
   553.2 1415.96   969.1 1414.62   984.7 1420.03  1002.4 1421.16  1106.4 1419.96
  1257.8 1423.04  1279.7 1420.61    1315 1423.07  1385.3 1422.29  1429.4 1413.89
  3121.4 1412.03  3195.4 1420.52  3457.4 1427.36  3585.5 1419.87  3718.5 1427.83
  3779.3  1429.1  3824.8 1435.38  3846.6 1444.23  3861.6 1455.38  3880.3 1458.33
  3910.2 1484.05  3929.1 1497.79  3943.8 1504.82  3969.7 1512.154093.897 1532.43
#Mann= 9 ,-1 , 0
       0      .1       0   284.1     .04       0   553.2    .045       0
   969.1      .1       0  1429.4    .045       0  3121.4    .025       0
  3195.4      .1       0  3457.4     .04       0  3718.5      .1       0
Bank Sta=553.2,3121.4
XS Rating Curve= 0 ,0
Exp/Cntr(USF)=0,0
Exp/Cntr=0.3,0.1
Stream Node=INDIANCK        ,Main            , 0 , 0 ,Upstream end
Stream Node=INDIANCK        ,Main            , 0 , 1 ,Downstream end
LCMann Table=0

Chan Stop Cuts=-1
Use User Specified Reach Order=0
Composite Channel Slope=5